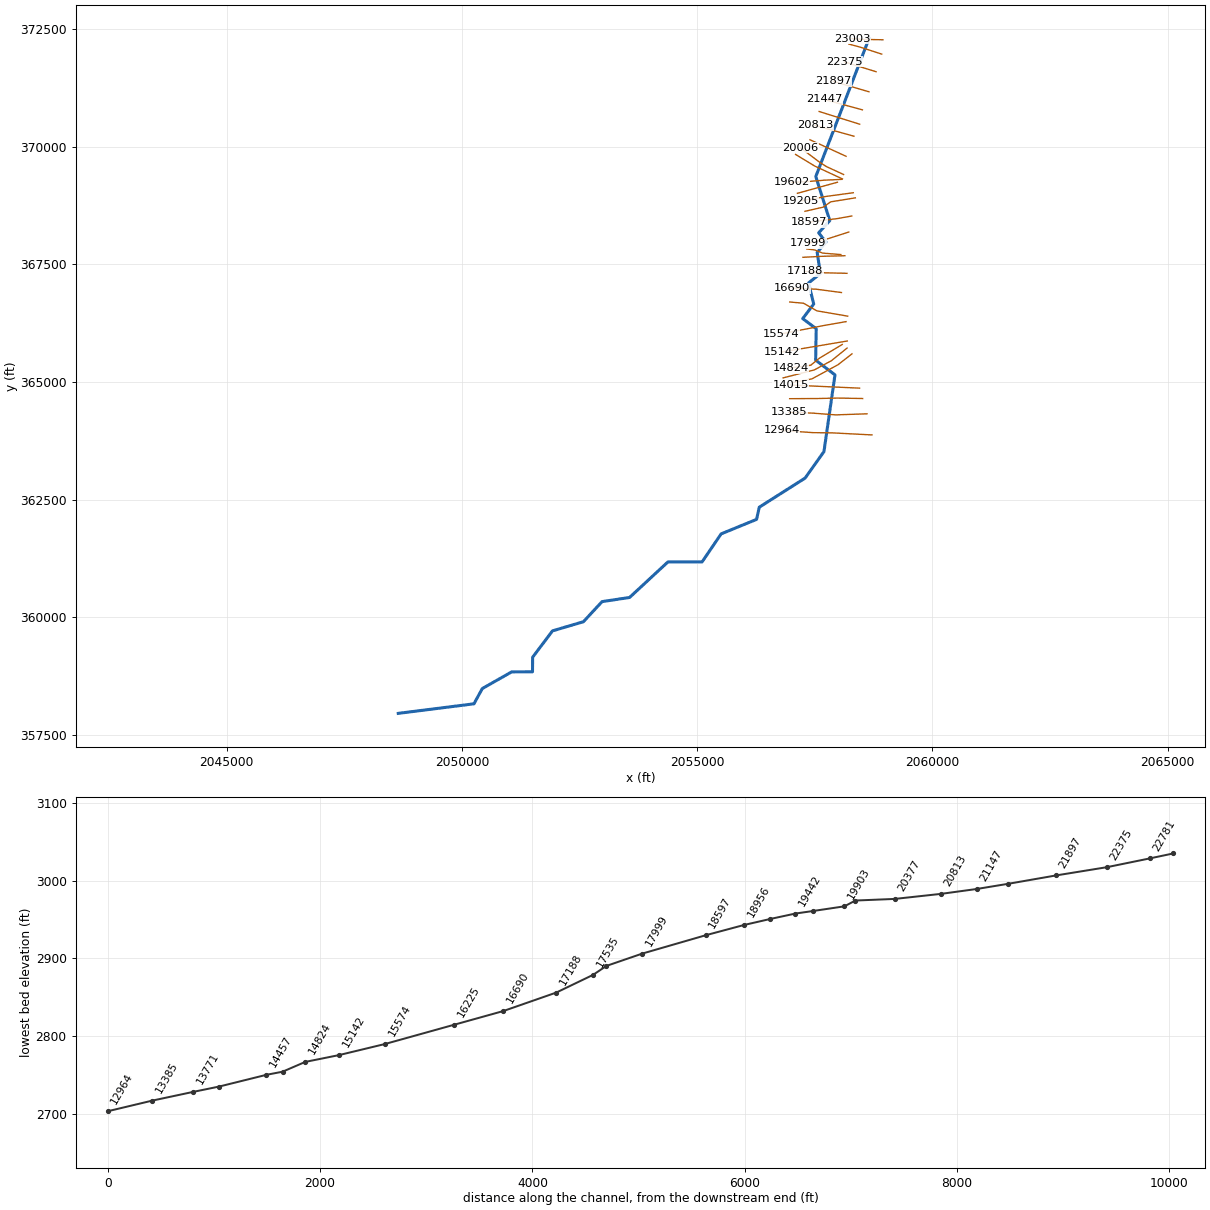
--- MILLCK2.prj (project) ---

Proj Title=MILLCK2
Current Plan=p01
Default Exp/Contr=0,0
English Units
Geom File=g01
Flow File=f01
Plan File=p01
BEGIN DESCRIPTION:
Mill Creek 2
Greenbrier County, WV
WV Disaster Studies / PMR
WVDHSEM-2017-2, Flood Risk Project
Type of Model: 1D Steady
HEC-RAS Version: 5.0.7
Upstream Extents:
Downstream Extents:
END DESCRIPTION:
DSS File=dss
DSS Export Rating Curves= 0
DSS Export Rating Curve Sorted= 0
DSS Export Volume Flow Curves= 0
DXF Filename=MILLCK.
DXF OffsetX= 0
DXF OffsetY= 0
DXF ScaleX= 0
DXF ScaleY= 0

--- MILLCK2.p01 (plan) ---

Plan Title=Floodplain
Program Version=5.07
Short Identifier=Floodplain
Geom File=g01
Flow File=f01
Subcritical Flow
K Sum by GR= 0
Std Step Tol= 0.01
Critical Tol= 0.01
Num of Std Step Trials= 20
Max Error Tol= 0.3
Flow Tol Ratio= 0.001
Split Flow NTrial= 30
Split Flow Tol= 0.02
Split Flow Ratio= 0.02
Log Output Level= 0
Friction Slope Method= 1
Unsteady Friction Slope Method= 2
Unsteady Bridges Friction Slope Method= 1
Parabolic Critical Depth
Global Vel Dist= 0 , 0 , 0
Global Log Level= 0
CheckData=True
Encroach Param=-1 ,0,0, 0
Computation Interval=0.1SEC
Output Interval=1MIN
Instantaneous Interval=Max Profile
Mapping Interval=1HOUR
Computation Time Step Use Courant=        0
Computation Time Step Use Time Series=    0
Computation Time Step Count To Double=0
Computation Time Step Max Doubling=0
Computation Time Step Max Halving=0
Computation Time Step Residence Courant=0
Run HTab= 0
Run UNet= 0
Run Sediment= 0
Run PostProcess= 0
Run WQNet= 0
Run RASMapper= 0
UNET Theta= 0
UNET Theta Warmup= 0
UNET ZTol= 0
UNET ZSATol= 0
UNET MxIter= 0
UNET Max Iter WO Improvement= 0
UNET MaxInSteps= 0
UNET DtIC= 0
UNET DtMin= 0
UNET MaxCRTS= 0
UNET WFStab= 0
UNET SFStab= 0
UNET WFX= 1
UNET SFX= 1
UNET 1D Methodology=Finite Difference
UNET DSS MLevel= 1
UNET Pardiso=0
UNET DZMax Abort= 0
UNET Use Existing IB Tables= 0
UNET Froude Reduction=False
UNET Froude Limit= 0
UNET Froude Power= 0
UNET D1 Cores= 0
UNET D2 Coriolis=0
UNET D2 Cores= 0
UNET D2 Theta= 1
UNET D2 Theta Warmup= 1
UNET D2 Z Tol= 0.01
UNET D2 Volume Tol= 0.01
UNET D2 Max Iterations= 20
UNET D2 Equation= 0
UNET D2 RampUpFraction=0.1
UNET D2 TimeSlices= 1
UNET D2 BCVolumeCheck=0
UNET D1D2 MaxIter= 0
UNET D1D2 ZTol=0.01
UNET D1D2 QTol=0.1
UNET D1D2 MinQTol=1
DSS File=dss
Write IC File= 0
Write IC File at Fixed DateTime=0
Write IC File at Sim End=0
Echo Input=False
Echo Parameters=False
Echo Output=False
Write Detailed= 0
HDF Write Warmup=0
HDF Write Time Slices=0
HDF Flush=0
HDF Face Node Velocities=0
HDF Compression= 1
HDF Chunk Size= 1
HDF Spatial Parts= 1
HDF Use Max Rows=0
HDF Fixed Rows= 1
Calibration Method= 0
Calibration Iterations= 20
Calibration Max Change=0.05
Calibration Tolerance=0.2
Calibration Maximum=1.5
Calibration Minimum=0.5
Calibration Optimization Method= 1
WQ AD Non Conservative
WQ ULTIMATE=-1
WQ Max Comp Step=1HOUR
WQ Output Interval=15MIN
WQ Output Selected Increments= 0
WQ Output face flow=0
WQ Output face velocity=0
WQ Output face area=0
WQ Output face dispersion=0
WQ Output cell volume=0
WQ Output cell surface area=0
WQ Output cell continuity=0
WQ Output cumulative cell continuity=0
WQ Output face conc=0
WQ Output face dconc_dx=0
WQ Output face courant=0
WQ Output face peclet=0
WQ Output face adv mass=0
WQ Output face disp mass=0
WQ Output cell mass=0
WQ Output cell source sink temp=0
WQ Output nsm pathways=0
WQ Output nsm derived pathways=0
WQ Output MaxMinRange=-1
WQ Daily Max Min Mean=-1
WQ Daily Range=0
WQ Daily Time=0
WQ Create Restart=0
WQ Fixed Restart=0
WQ System Summary=0
WQ Write To DSS=0
WQ Use Fixed Temperature=0
Sorting and Armoring Iterations= 10
XS Update Threshold= 0.02
Bed Roughness Predictor= 0
Hydraulics Update Threshold= 0.02
Energy Slope Method= 1
Volume Change Method= 1
Sediment Retention Method= 0
XS Weighting Method= 0
Number of US Weighted Cross Sections= 1
Number of DS Weighted Cross Sections= 1
Upstream XS Weight=0
Main XS Weight=1
Downstream XS Weight=0
Number of DS XS's Weighted with US Boundary= 1
Upstream Boundary Weight= 1
Weight of XSs Associated with US Boundary= 0
Number of US XS's Weighted with DS Boundary= 1
Downstream Boundary Weight= 0.5
Weight of XSs Associated with DS Boundary= 0.5
Percentile Method= 0
Sediment Output Level= 3
Mass or Volume Output= 0
Output Increment Type= 1
Profile and TS Output Increment= 1
XS Output Flag= 0
XS Output Increment= 10
Write Gradation File= 0
Read Gradation Hotstart= 0
Write HDF5 File= 1
Write Binary Output= 1
Write DSS Sediment File= 0
SV Curve= 0
Specific Gage Flag= 0

--- MILLCK2.f01 (steady flow) ---

Flow Title=NFF Regression Equation
Program Version=5.07
Number of Profiles= 6
Profile Names=f1p,f10p,f4p,f2p,f02p,f1pplus
River Rch & RM=MILLCK,Main            ,23003
     598     317     421     507     835     885
River Rch & RM=MILLCK,Main            ,20813
     715     381     505     606     995    1060
River Rch & RM=MILLCK,Main            ,19205
     862     463     611     732    1190    1270
River Rch & RM=MILLCK,Main            ,14015
    1090     588     772     924    1500    1610
River Rch & RM=MILLCK,Main            ,8609
    1240     673     883    1050    1700    1830
River Rch & RM=MILLCK,Main            ,7713
    1380     753     986    1180    1890    2040
Boundary for River Rch & Prof#=MILLCK,Main            , 1
Up Type= 0
Dn Type= 3
Dn Slope=0.015056
DSS Import GetInterval= 0
DSS Import GetPeak= 0
DSS Import FillOption= 0

--- MILLCK2.g01 (geometry) ---

Geom Title=USGS 10m DEM
Program Version=5.07

River Reach=MILLCK          ,Main
Reach XY= 30
2058653.61696194372299.1710877122057520.92500161369363.433848962
2057818.26397385368426.1420883832057582.27986576368166.532043293
2057738.23132552367969.6676076352057550.84456117367750.459712714
2057618.03438742367302.2585093832057367.22386543367101.477086797
2057476.69904019366653.0075112882057243.20967777366343.846384212
2057529.99552153366129.2841492892057518.11726443 365461.77662605
2057928.51080061365148.7900472882057695.04013894363518.853346542
2057294.09343426362955.410903871 2056319.7423646362336.558138967
2056262.47902767362078.1639707092055509.75513943361770.002513543
2055104.71986027361174.9771287892054378.98476319361174.599504873
2053563.57661711360418.7476701292052979.04136886360330.515891209
2052582.73376252359903.3274411262051925.88140167359709.439377457
2051503.33073761359149.3742246332051500.63947003358839.204241291
2051057.25124918358837.8587715482050433.63996361358482.803051218
2050256.05042376358159.2515329572048647.76000519357956.060994461

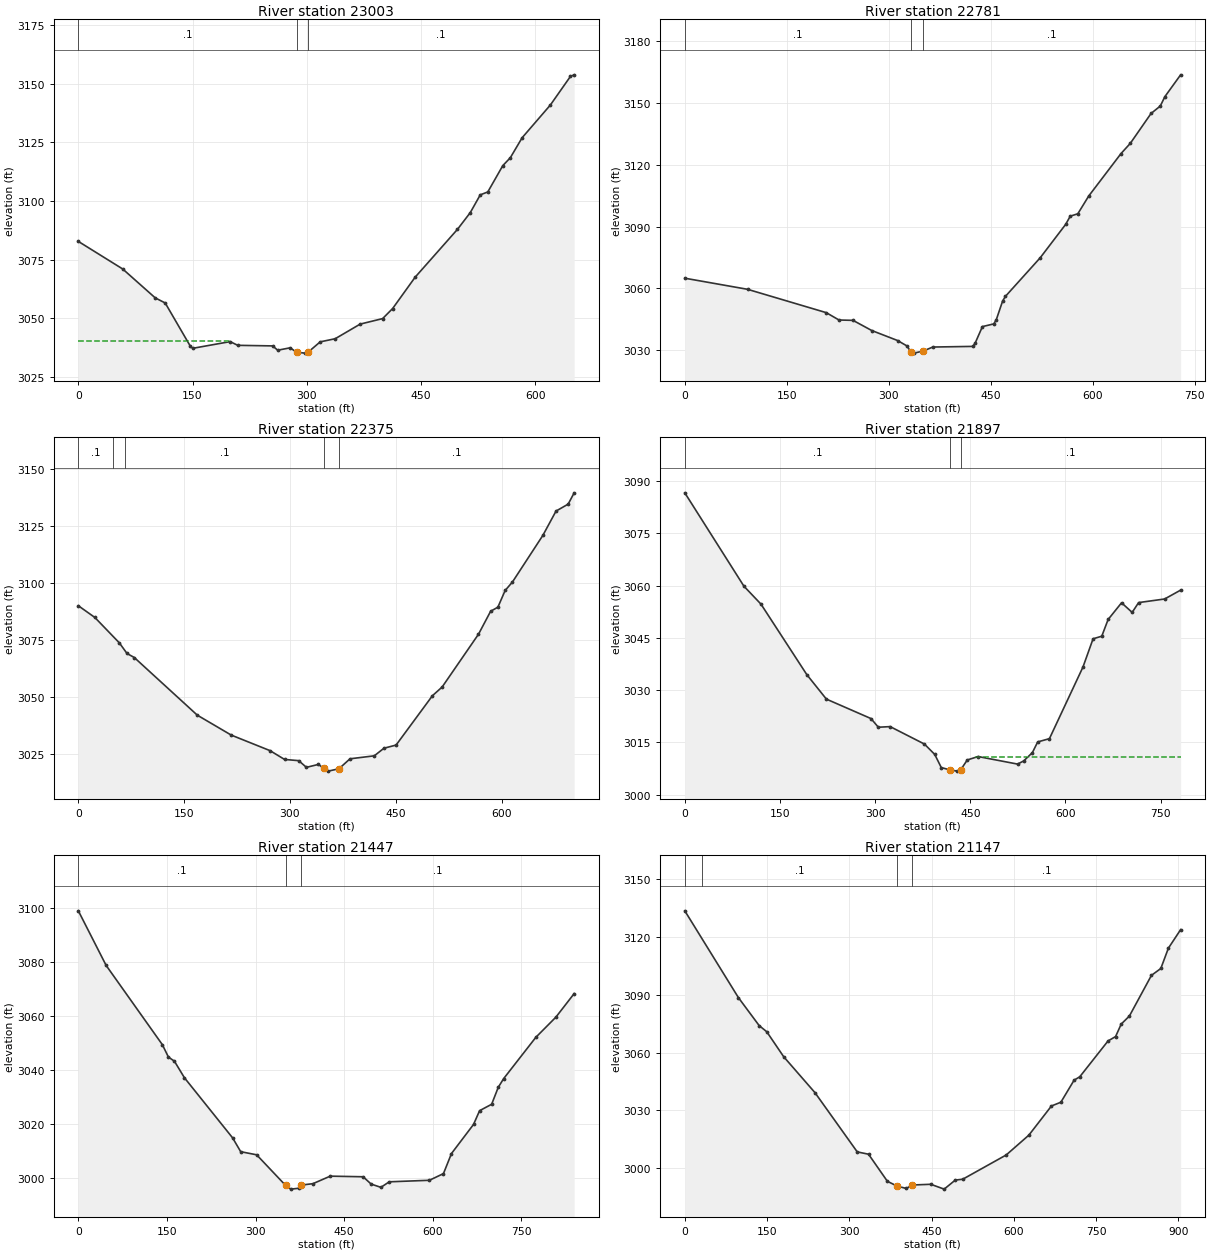
Type RM Length L Ch R = 1 ,23003   ,223.9,222,219.4
XS GIS Cut Line= 3
      2058948.16       372268.74     2058538.368      372276.259
     2058297.757      372293.177
#Sta/Elev= 30
       0 3082.72    58.3 3070.95     101 3058.63   114.1 3056.45   146.9 3038.12
   150.2 3037.12   199.4 3039.98   209.3  3038.4   255.2 3038.15   261.8 3036.31
   278.2 3037.34   286.83035.402   297.9 3035.07   301.8 3035.49   317.6 3039.88
   337.3 3041.21   370.1 3047.45   399.6  3049.8   412.7 3054.08   442.3 3067.46
   497.9 3087.88   514.7 3095.01   527.8 3102.58   537.7 3103.82   557.4 3115.04
   567.3 3118.42   582.8 3126.95   619.9 3140.91   646.2 3153.09   651.1 3153.77
#Mann= 3 ,-1 , 0
       0      .1       0   286.8    .045       0   301.8      .1       0
#XS Ineff= 2 , 0
          199.64 3040.32
Permanent Ineff=
       F       F
Bank Sta=286.8,301.8
XS Rating Curve= 0 ,0
Exp/Cntr=0.3,0.1

Type RM Length L Ch R = 1 ,22781   ,404.5,405.7,404.5
XS GIS Cut Line= 3
     2058921.843      371964.216     2058463.177      372112.719
     2058224.445      372176.631
#Sta/Elev= 30
       0 3064.97    92.3 3059.59     208 3048.28   226.8 3044.71   247.4 3044.54
     275 3039.61     313 3034.76   326.8 3032.12   332.3 3029.31   337.1 3028.66
   350.9 3029.71   364.7 3031.61   423.3 3031.92   426.8 3033.35   437.7 3041.52
   454.4 3042.82   458.1 3044.85   467.4 3053.89   471.6 3056.19   522.7 3074.87
   560.1 3091.04   566.9 3095.05     578 3096.18     594 3104.78   641.6  3125.4
   655.2 3130.32   685.7 3144.79   699.3 3148.41   706.1 3152.98   729.2 3163.53
#Mann= 3 ,-1 , 0
       0      .1       0   332.3    .045       0   350.9      .1       0
Bank Sta=332.3,350.9
XS Rating Curve= 0 ,0
Exp/Cntr=0.3,0.1

Type RM Length L Ch R = 1 ,22375   ,476.5,477.6,475.3
XS GIS Cut Line= 2
     2058801.537       371590.14     2058130.456      371798.796
#Sta/Elev= 30
       0 3090.02    23.4 3084.87    58.2 3073.67      69 3069.03    79.3 3067.26
   168.6 3041.92   216.7 3033.16   271.7 3026.32   292.3 3022.45   312.4 3021.91
   323.3 3018.97   340.4 3020.27   347.63018.552   354.2 3017.31   369.43018.346
   385.1 3022.73   419.5 3024.04   433.2 3027.38   450.4 3028.77   501.9 3050.46
   515.7  3054.3   567.2  3077.5   584.4 3087.59   594.7 3089.39     605 3096.75
   615.3 3100.44   658.4 3120.93   677.1 3131.64   694.3 3134.69   702.8 3139.66
#Mann= 5 ,-1 , 0
       0      .1       0   48.66      .1       0   66.48      .1       0
   347.6    .045       0   369.4      .1       0
Bank Sta=347.6,369.4
XS Rating Curve= 0 ,0
Exp/Cntr=0.3,0.1

Type RM Length L Ch R = 1 ,21897   ,445.1,449.9,443.4
XS GIS Cut Line= 2
     2058651.155       371163.43     2057901.123      371383.365
#Sta/Elev= 30
       0 3086.68    93.2 3059.86   120.1  3054.7   192.3 3034.46   223.2 3027.42
   293.5 3021.83   305.1 3019.34   323.7 3019.52   377.7 3014.51     394 3011.53
   404.3 3007.75   418.13007.084   429.4 3006.73     4353007.135   445.3 3009.94
   462.4 3010.92   524.6 3008.75   534.2 3009.66   547.9 3012.04   556.3 3015.12
   574.8 3016.06   627.7 3036.65   643.6 3044.75   657.3 3045.49   667.3 3050.29
   688.5 3055.09   705.2 3052.33   715.4 3055.15   756.4 3056.18   781.6 3058.73
#Mann= 3 ,-1 , 0
       0      .1       0   418.1    .045       0     435      .1       0
#XS Ineff= 2 , 0
                          458.23         3010.84
Permanent Ineff=
       F       F
Bank Sta=418.1,435
XS Rating Curve= 0 ,0
Exp/Cntr=0.3,0.1

Type RM Length L Ch R = 1 ,21447   ,299.8,299.9,299.1
XS GIS Cut Line= 2
     2058512.051      370779.956     2057701.867       370999.89
#Sta/Elev= 30
       0 3099.13    47.1 3078.89   142.3 3049.51   152.5 3044.94   162.7 3043.39
   179.7 3037.24   261.3 3014.95   274.9 3009.86   301.9  3008.7   350.92997.365
   359.8 2995.98   373.4  2996.3   377.12997.471   397.2    2998   426.5 3000.79
   482.2 3000.56   495.8 2997.85   512.3 2996.64   526.4 2998.69   594.4 2999.26
   618.2 3001.73   631.8 3009.18   669.2 3019.98   679.4 3025.06   699.8 3027.43
     711 3033.72   720.2 3036.96   774.6 3052.24   808.6 3059.73   839.5 3068.46
#Mann= 3 ,-1 , 0
       0      .1       0   350.9    .045       0   377.1      .1       0
#XS Ineff= 2 , 0
                          476.54          3000.2
Permanent Ineff=
       F       F
Bank Sta=350.9,377.1
XS Rating Curve= 0 ,0
Exp/Cntr=0.3,0.1

Type RM Length L Ch R = 1 ,21147   ,327.3,334.7,330.8
XS GIS Cut Line= 2
 2058454.9619209370474.4320636162057592.26885573370744.717873733
#Sta/Elev= 30
       0 3133.44    97.8 3088.44   135.6 3073.96   149.4 3070.79   180.3 3057.83
   237.3 3039.23   314.4 3008.52     335 3007.31   369.4 2993.26   386.6 2990.87
   403.8 2989.56   414.92991.354   448.5 2991.73   472.9 2989.22   493.2 2993.91
   506.8 2994.36     586 3006.92   627.3 3017.19   668.5 3032.31   685.7 3034.26
   709.8  3045.7   720.1 3047.43   771.7 3066.02   785.4 3068.27   795.7 3074.75
   810.6 3078.92   850.8    3100   867.9 3103.56   881.7 3114.09     904 3123.69
#Mann= 4 ,-1 , 0
       0      .1       0   32.27      .1       0   386.6    .045       0
   414.9      .1       0
Bank Sta=386.6,414.9
XS Rating Curve= 0 ,0
Exp/Cntr(USF)=0,0
Exp/Cntr=0.3,0.1

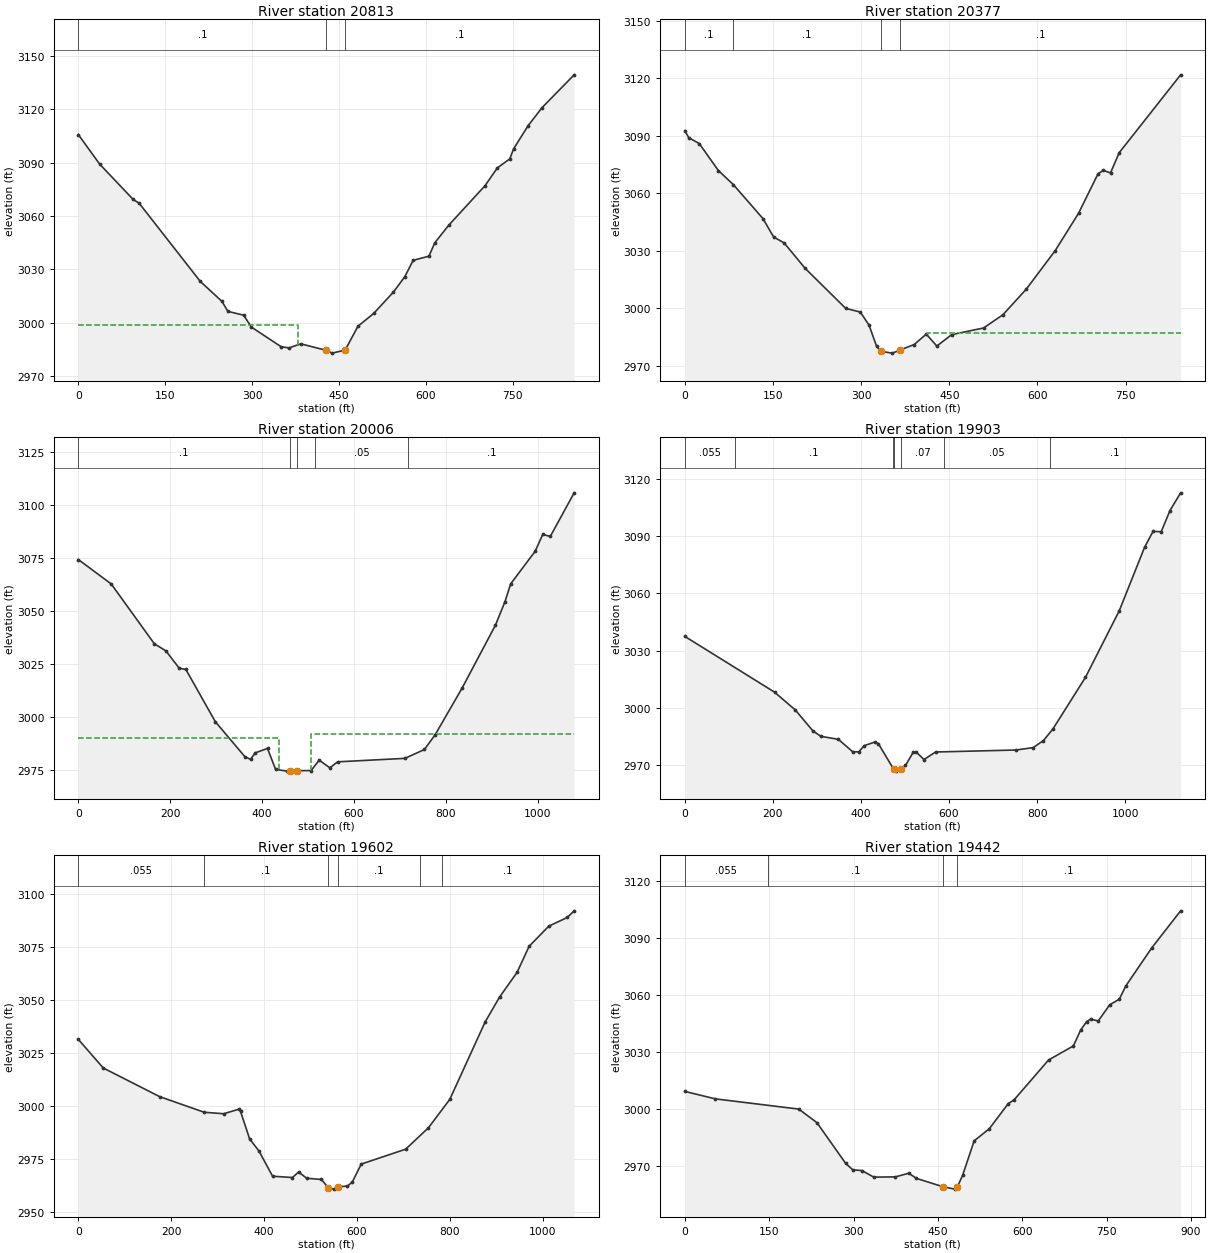
Type RM Length L Ch R = 1 ,20813   ,433.4,435.9,429
XS GIS Cut Line= 2
     2058331.593      370219.782      2057506.37      370449.115
#Sta/Elev= 30
       0  3105.7    36.9  3089.1    94.8 3069.25     105 3067.18   210.6 3023.27
   248.1 3012.03   258.3 3006.43   285.5 3004.28   299.1 2997.57   350.2 2986.59
   363.8 2985.89   384.3 2988.19   428.22984.536   438.6 2982.97   460.92984.674
     483 2998.05   510.3 3005.29   544.3 3017.25     564 3025.92   578.4 3035.11
   605.6  3037.4   615.8 3044.95   639.7 3054.75   702.5    3077   723.8 3086.96
   745.2 3092.05     752 3097.76   777.1 3110.75   801.1 3120.87   856.5 3139.26
#Mann= 3 ,-1 , 0
       0      .1       0   428.2    .045       0   460.9      .1       0
#XS Ineff= 2 , 0
          378.74 2998.58
Permanent Ineff=
       F       F
Bank Sta=428.2,460.9
XS Rating Curve= 0 ,0
Exp/Cntr=0.3,0.1

Type RM Length L Ch R = 1 ,20377   ,371.1,370.7,368.7
XS GIS Cut Line= 2
     2058164.292      369793.072     2057397.343      370144.591
#Sta/Elev= 30
       0 3092.77     6.7 3089.07    24.7 3085.96    57.2 3071.87    82.5 3064.56
     133 3046.79   151.1 3037.18   169.1 3034.06   204.7 3020.81   273.8 2999.86
   298.7 2997.92   313.5  2991.1   326.4 2980.03   333.52977.401   353.2 2976.47
   366.22978.085   390.3 2980.97   410.9 2986.39   428.9 2980.17   454.2 2986.14
   508.3  2989.6   541.3 2996.52   580.9 3009.85   630.4 3030.08     670 3049.56
   703.2  3070.2     712 3071.97   724.4 3070.67   739.2 3081.23   843.7 3121.91
#Mann= 4 ,-1 , 0
       0      .1       0    82.5      .1       0   333.5    .045       0
   366.2      .1       0
#XS Ineff= 2 , 0
                          411.96         2987.02
Permanent Ineff=
       F       F
Bank Sta=333.5,366.2
XS Rating Curve= 0 ,0
Exp/Cntr=0.5,0.3

Type RM Length L Ch R = 1 ,20006   ,102,102.9,103.9
XS GIS Cut Line= 4
     2058111.658      369405.838     2057748.861      369573.138
     2057611.637      369659.608     2057198.086      369971.651
#Sta/Elev= 30
       0 3074.33    71.6 3062.82   165.5 3034.56   190.8 3031.18   219.7 3023.02
   234.2 3022.41   298.4 2997.73   362.7 2981.23   375.1 2979.95     385 2983.02
     412  2985.1   429.6 2975.21   454.7  2974.4   460.42974.539   475.42974.621
   506.9 2974.66   524.5 2979.58   547.8 2975.96   564.7 2978.79   711.3 2980.43
   753.7 2984.62   777.1 2991.59   835.7  3013.6   908.3 3043.31   929.2 3054.47
   941.5 3062.84     995 3078.29  1011.3 3086.19  1027.8 3085.25  1079.8 3105.85
#Mann= 5 ,-1 , 0
       0      .1       0   460.4    .045       0   475.4      .1       0
  515.18     .05       0  718.85      .1       0
#XS Ineff= 2 , 0
          437.21  2990.2  506.31         2991.94
Permanent Ineff=
       F       F
Bank Sta=460.4,475.4
XS Rating Curve= 0 ,0
Exp/Cntr=0.5,0.3

Type RM Length L Ch R = 1 ,19903   ,294.2,300.8,306
XS GIS Cut Line= 3
     2058087.221      369311.849     2057496.971      369586.296
     2057090.939      369832.547
#Sta/Elev= 30
       0 3037.52   203.9 3008.29     251 2998.95   290.8 2988.02   308.9 2985.17
   348.7 2983.59   381.2 2977.09   394.9 2977.02   407.3 2980.26   431.9 2982.22
   439.4 2981.35   474.32967.933   478.9 2966.94   491.92968.169   501.1 2969.91
   518.7 2976.83   525.8 2976.84   543.1    2973   569.4 2976.96   752.1    2978
   790.8 2979.24   814.2 2982.91   835.7 2988.97   909.8 3016.08   986.5 3050.95
  1044.1 3084.26  1063.2 3092.51  1081.7 3092.33  1101.6 3103.41  1125.8  3112.7
#Mann= 7 ,-1 , 0
       0    .055       0  112.95      .1       0  472.01    .055       0
   474.3    .045       0   491.9     .07       0  589.02     .05       0
  828.89      .1       0
Bank Sta=474.3,491.9
XS Rating Curve= 0 ,0
Exp/Cntr=0.5,0.3

Type RM Length L Ch R = 1 ,19602   ,155.9,160.5,161.3
XS GIS Cut Line= 4
     2058074.063       369302.45     2057709.386      369285.532
     2057361.627      369257.335     2057008.228      369238.537
#Sta/Elev= 30
       0 3031.33    53.7 3017.86   175.2 3004.37   271.2 2997.02   313.2 2996.32
     346 2998.48   349.3 2997.47     369 2984.42   388.8 2978.86   418.4  2966.9
   461.2 2966.29   474.3 2968.88   491.8 2965.95   523.7 2965.36   537.92961.548
     550 2960.82   560.22961.956   579.7 2962.26   589.9  2964.1   609.3 2972.61
     705 2979.63   754.1 2989.73   800.1 3003.11   876.3 3039.61   907.5 3051.35
     945 3062.92   970.9 3075.18  1013.3 3084.67    1053 3088.74  1067.9 3091.88
#Mann= 6 ,-1 , 0
       0    .055       0  271.39      .1       0   537.9    .045       0
   560.2      .1       0  735.65     .07       0  782.93      .1       0
Bank Sta=537.9,560.2
XS Rating Curve= 0 ,0
Exp/Cntr=0.3,0.1

Type RM Length L Ch R = 1 ,19442   ,234,236.8,233.3
XS GIS Cut Line= 2
2057981.03611686369241.484464039 2057131.3019604 369006.37283469
#Sta/Elev= 30
       0 3009.16    54.5 3005.22   202.7 2999.84   234.9 2992.72   285.9  2971.3
   298.7 2967.83   314.7 2967.46     336 2963.99   374.4 2964.11   398.3 2966.04
   411.9 2963.32   458.6 2958.97     480 2957.66   484.7 2958.82   494.1    2965
   514.6 2983.14   541.3 2989.42   575.3 3002.76   585.5 3004.68   646.8  3025.7
     691 3033.13   703.9 3041.49   714.6 3045.93   721.7 3047.24   735.3 3046.31
   755.7 3054.86   772.7 3057.74   783.9  3064.6   830.6 3084.91   881.7 3104.33
#Mann= 4 ,-1 , 0
       0    .055       0  147.97      .1       0   458.6    .045       0
   484.7      .1       0
Bank Sta=458.6,484.7
XS Rating Curve= 0 ,0
Exp/Cntr(USF)=0,0
Exp/Cntr=0.3,0.1

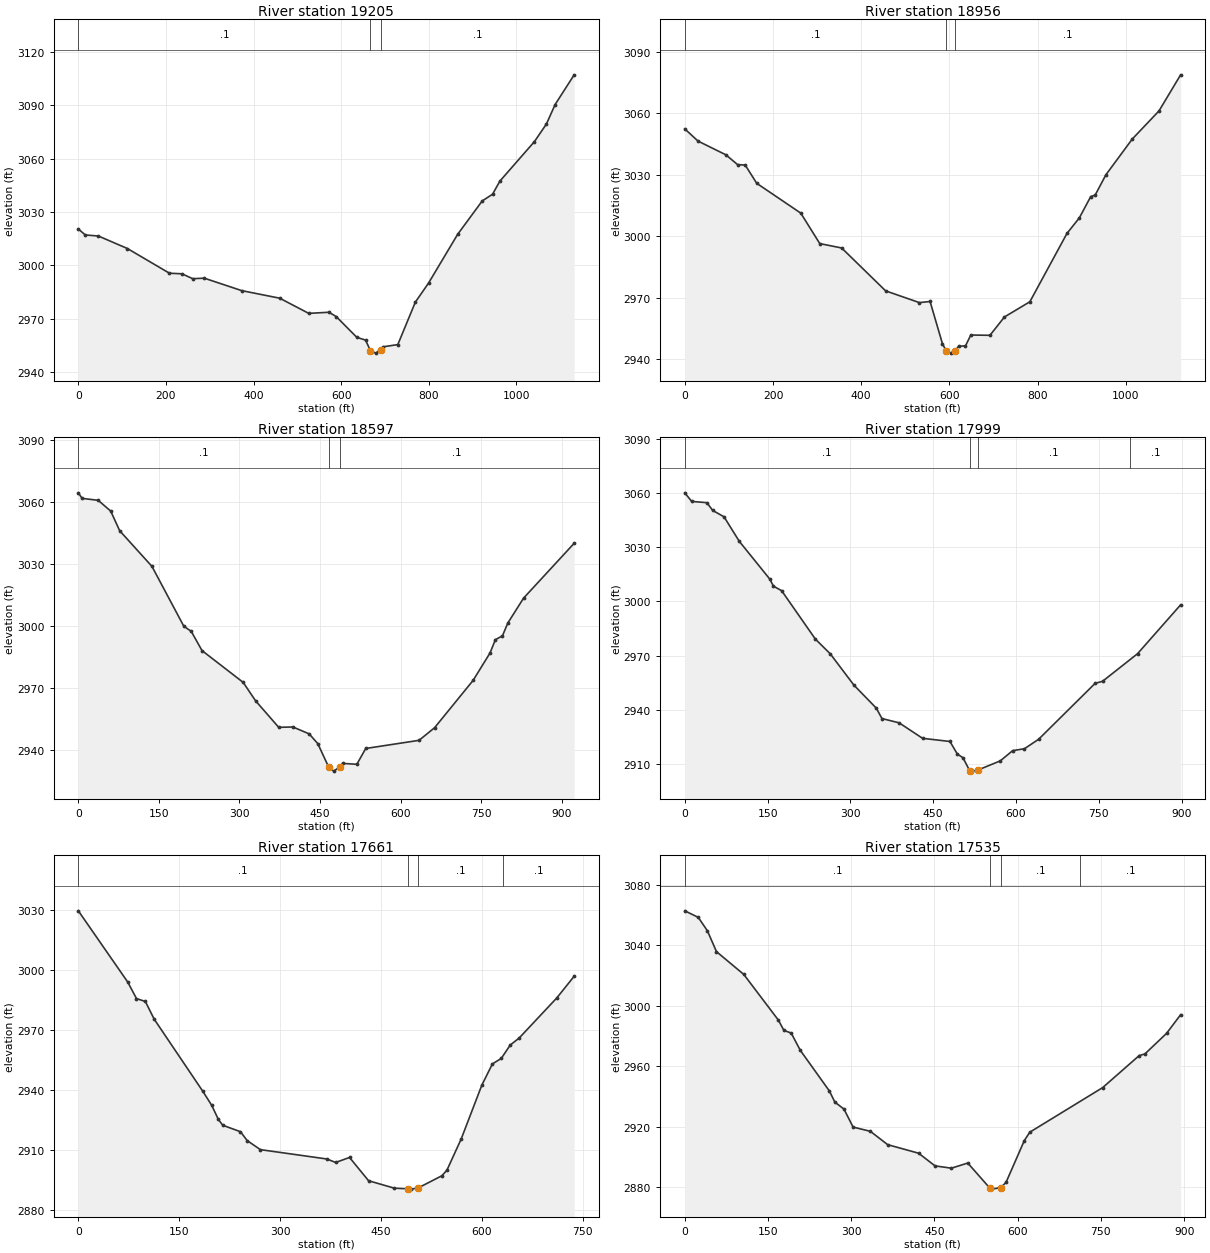
Type RM Length L Ch R = 1 ,19205   ,242.7,249,251.3
XS GIS Cut Line= 4
     2058318.434      369018.603     2057735.703      368939.653
     2057523.288      368898.297     2057199.966      368847.543
#Sta/Elev= 30
       0  3020.4      16 3017.05    45.8 3016.46     112 3009.44     208 2995.56
   236.5 2995.24     261 2992.49   287.5 2992.78     373 2985.78   459.7 2981.53
   525.9 2973.01   572.2 2973.64   588.7 2971.19   635.6 2959.55   655.6 2957.99
   666.82952.007     679 2950.68   689.72952.637   695.7 2954.24   729.2 2955.47
   769.3 2979.36   799.4 2990.04   865.8 3017.42   921.8 3036.15   945.5 3039.95
   962.1 3047.28  1041.1 3069.52  1068.4 3079.38  1088.3 3090.33  1131.7    3107
#Mann= 3 ,-1 , 0
       0      .1       0   666.8    .045       0   689.7      .1       0
Bank Sta=666.8,689.7
XS Rating Curve= 0 ,0
Exp/Cntr=0.3,0.1

Type RM Length L Ch R = 1 ,18956   ,361.8,359.5,352.4
XS GIS Cut Line= 4
     2058361.669      368909.576     2057837.211      368824.986
      2057677.43      368712.199     2057290.195       368623.85
#Sta/Elev= 30
       0 3052.29      30 3046.35    93.1 3039.65   119.7 3034.86     137 3034.64
   163.1 3025.74   262.9  3011.2     306 2996.33   355.6 2994.19   455.3 2973.26
   531.8 2967.53     556 2968.08   584.1 2947.45   593.22943.744   602.4 2942.88
   612.72944.099   621.2 2946.28   636.3 2946.39   648.3 2951.71   691.8 2951.58
   724.6 2960.52   782.2 2967.94   866.3 3001.28   894.4 3008.87   920.2 3019.27
   930.3    3020   954.6  3029.9  1014.4 3047.35    1075 3061.08    1124 3078.68
#Mann= 3 ,-1 , 0
       0      .1       0   593.2    .045       0   612.7      .1       0
Bank Sta=593.2,612.7
XS Rating Curve= 0 ,0
Exp/Cntr=0.3,0.1

Type RM Length L Ch R = 1 ,18597   ,596.5,597.4,595.4
XS GIS Cut Line= 3
     2058286.478      368524.222     2057981.954      368469.708
     2057372.906      368392.637
#Sta/Elev= 30
       0  3064.5       7 3061.82      37 3060.87    60.3 3055.65      77 3046.14
     137 3028.91   196.4  2999.9   210.3  2997.4   230.3  2988.1     307 2972.69
   330.1 2963.77   373.1 2950.94   399.6  2951.1   429.9 2947.76   445.9 2943.04
   466.12931.724   475.6 2929.72   486.42931.649   492.2 2933.46   518.6 2933.03
   535.2 2940.69   634.4 2944.63   663.4 2950.74   735.2 2973.69   766.6 2986.93
   776.6 2993.36   789.8 2995.27   799.7 3001.41   829.1  3013.5   923.3 3040.06
#Mann= 3 ,-1 , 0
       0      .1       0   466.1    .045       0   486.4      .1       0
Bank Sta=466.1,486.4
XS Rating Curve= 0 ,0
Exp/Cntr=0.3,0.1

Type RM Length L Ch R = 1 ,17999   ,339.3,338.3,329.9
XS GIS Cut Line= 3
     2058222.565      368183.982     2057803.375      368048.638
     2057357.867       367943.37
#Sta/Elev= 30
       0 3060.01    12.5 3055.26      40 3054.57    50.5 3050.29    71.1 3046.74
    98.7  3033.2   153.8 3012.38   160.7 3008.37   175.4 3005.92   236.6 2979.12
   263.6 2970.97   306.3 2953.71   346.9 2940.96   357.2  2935.2   388.3 2932.83
   430.8 2924.26   480.4 2922.51   493.9 2915.49     504 2913.54     5162906.429
   520.9 2906.12     531 2906.72   571.5 2911.78     594 2917.45   615.3  2918.5
     641 2923.73   743.4 2954.66   756.9  2955.8   820.3 2971.07   898.3 2998.08
#Mann= 4 ,-1 , 0
       0      .1       0     516    .045       0     531      .1       0
  806.74      .1       0
Bank Sta=516,531
XS Rating Curve= 0 ,0
Exp/Cntr=0.3,0.1

Type RM Length L Ch R = 1 ,17661   ,122.5,126.3,126.4
XS GIS Cut Line= 4
     2058054.157      367704.393     2057665.749      367735.862
     2057496.719      367803.294     2057332.186      367823.973
#Sta/Elev= 30
       0 3029.43    73.4 2993.84    86.5 2985.55    99.7 2984.08   112.8 2975.25
   185.3 2939.09   198.4 2932.14   208.3 2925.06   214.9 2922.16   241.2 2918.94
   251.1 2914.52   270.8 2909.97   369.6  2905.3   382.8 2903.56   403.4 2906.06
   431.7 2894.42     470  2890.7   490.52890.397     495 2890.22   505.52890.827
   540.7  2896.9   548.3 2899.73   569.5 2915.33   600.2 2942.25   615.9 2952.85
   629.1  2955.6   642.4 2962.29   655.6 2965.76   711.8 2985.91   737.5 2996.71
#Mann= 4 ,-1 , 0
       0      .1       0   490.5    .045       0   505.5      .1       0
  631.73      .1       0
Bank Sta=490.5,505.5
XS Rating Curve= 0 ,0
Exp/Cntr=0.3,0.1

Type RM Length L Ch R = 1 ,17535   ,346.4,346,343.2
XS GIS Cut Line= 3
     2058139.855      367680.201     2057636.074      367667.043
      2057246.96      367646.365
#Sta/Elev= 30
       0 3062.89    24.3 3058.55    40.7 3049.69    57.1 3035.87   106.4 3020.76
   168.7 2990.52   178.6 2983.73   191.7    2982   208.1 2970.57   260.6 2943.62
   270.4 2936.28   286.9 2931.61   303.3 2919.72   334.4 2916.93   365.6  2908.1
   421.4 2902.42     451 2894.03   480.5 2892.52     510 2895.92   549.82879.315
   552.7 2878.65   569.4 2879.64     579 2883.16   611.9 2910.79   621.7 2916.32
   753.2 2945.89   818.9 2967.05   829.2 2968.14   868.2 2981.74   893.6 2994.12
#Mann= 4 ,-1 , 0
       0      .1       0   549.8    .045       0   569.4      .1       0
  713.11      .1       0
Bank Sta=549.8,569.4
XS Rating Curve= 0 ,0
Exp/Cntr=0.3,0.1

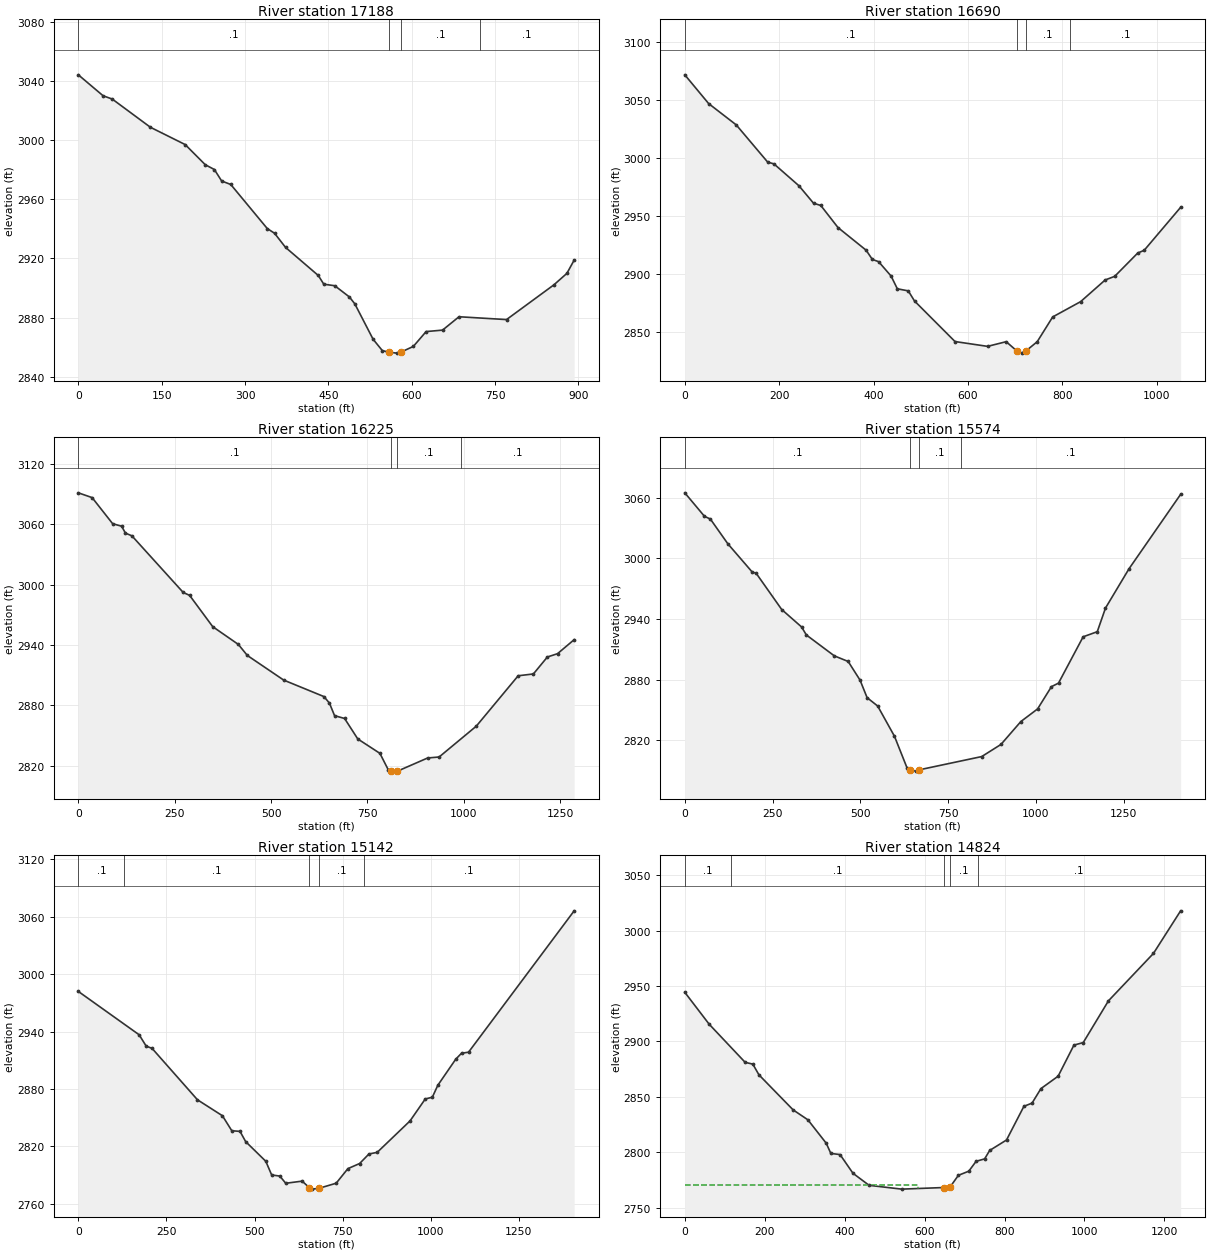
Type RM Length L Ch R = 1 ,17188   ,492,498.5,490.7
XS GIS Cut Line= 3
      2058183.09      367306.125     2057713.145      367317.404
     2057292.075       367347.48
#Sta/Elev= 30
       0 3044.34    44.6 3030.15      61 3027.94   129.7 3008.83   192.3 2997.11
   228.4 2983.48   244.8 2980.22   257.9 2972.46   274.3 2970.09   339.9 2940.29
   353.1 2937.06   372.8 2927.52   431.8 2908.47   441.7 2902.58   461.4 2901.55
   487.7 2893.96   497.5 2889.29   530.4 2865.31   546.9 2857.67   558.5 2856.52
   573.2 2855.91   581.32856.738   602.8 2860.45   625.8  2870.5   655.4 2871.49
     685 2880.54   770.5 2878.62   855.8 2902.16   879.1  2909.9   892.2 2918.89
#Mann= 4 ,-1 , 0
       0      .1       0   558.5    .045       0   581.3      .1       0
  721.88      .1       0
Bank Sta=558.5,581.3
XS Rating Curve= 0 ,0
Exp/Cntr=0.3,0.1

Type RM Length L Ch R = 1 ,16690   ,464,464.8,459.1
XS GIS Cut Line= 3
     2058066.544      366898.213     2057538.326      366967.765
     2057021.387      366992.202
#Sta/Elev= 30
       0 3072.09    50.5  3047.3     109 3028.92   175.6 2996.82   188.8 2995.32
   241.8 2976.43   272.7 2961.39   288.1 2959.45   324.5 2940.41   384.1 2920.88
   397.3 2912.91   410.5 2911.02     437 2898.59   450.2  2887.6   473.4 2885.82
   486.6 2877.09   572.4 2842.12   641.4 2837.97   680.8 2842.01   703.12834.119
   713.6 2832.14   722.82834.099   746.5 2841.97   779.3 2863.34   838.4 2876.51
   890.5 2895.22   910.7 2898.36   959.5 2918.46   973.1 2920.78  1050.3 2957.84
#Mann= 4 ,-1 , 0
       0      .1       0   703.1    .045       0   722.8      .1       0
  816.71      .1       0
Bank Sta=703.1,722.8
XS Rating Curve= 0 ,0
Exp/Cntr=0.3,0.1

Type RM Length L Ch R = 1 ,16225   ,644,651.7,654.6
XS GIS Cut Line= 4
     2058200.008      366396.312     2057543.965      366509.099
     2057260.119       366670.76     2056966.873      366697.077
#Sta/Elev= 30
       0 3091.32    35.8 3086.56      89 3060.62   112.3 3058.09   122.3 3051.23
     139 3048.54   272.1 2992.23   288.8 2989.29   348.7 2958.18   415.3 2940.48
   438.6 2929.51   532.8 2905.04   637.4  2888.6   651.6 2882.13   664.9 2869.65
     691 2866.81   725.2 2846.45   782.6 2832.13   804.2 2815.84   810.92814.806
   825.9 2814.55   828.3 2814.44   906.5 2827.52   936.3  2828.5  1032.7 2859.16
  1141.4 2909.31  1180.9 2911.12  1217.2    2928  1243.5 2931.27  1286.7 2945.24
#Mann= 4 ,-1 , 0
       0      .1       0   810.9    .045       0   825.9      .1       0
  993.72      .1       0
Bank Sta=810.9,825.9
XS Rating Curve= 0 ,0
Exp/Cntr=0.3,0.1

Type RM Length L Ch R = 1 ,15574   ,428.8,431.9,429.9
XS GIS Cut Line= 3
     2058164.292      366279.766      2057669.91      366193.296
     2056777.016      366016.597
#Sta/Elev= 30
       0  3064.7    56.1 3041.46    72.8  3038.8   122.7 3014.28   192.7 2986.13
   202.7 2985.46     276 2949.38   332.6 2932.12   346.2 2924.22   425.8 2903.57
   465.3 2898.02   499.1 2879.58   519.2 2862.24   549.3 2853.99   597.1 2824.13
   632.9 2792.87   642.72790.529   659.6 2789.64   665.62790.774   845.6 2804.03
   900.4 2816.01   957.2 2838.68  1004.7  2851.1  1044.2 2873.13  1064.3 2876.61
  1134.5 2922.41  1174.7 2927.43  1198.1 2950.79    1265 2989.58  1412.1 3063.18
#Mann= 4 ,-1 , 0
       0      .1       0   642.7    .045       0   665.6      .1       0
  787.97      .1       0
Bank Sta=642.7,665.6
XS Rating Curve= 0 ,0
Exp/Cntr=0.3,0.1

Type RM Length L Ch R = 1 ,15142   ,316.1,318,317.9
XS GIS Cut Line= 2
     2058190.609      365868.095     2056803.333      365635.002
#Sta/Elev= 30
       0 2981.87   172.6 2936.58   192.5 2924.75   209.2 2922.42     338 2868.71
   408.8 2852.04   435.4 2836.39   458.7 2835.72   474.7 2825.04   531.9 2804.47
   548.5 2790.21   571.6 2789.04   588.4 2781.53     635 2783.76   655.8  2776.8
   661.6 2775.41     682 2776.17   731.5 2781.59   764.8 2796.81     798 2802.14
   824.6 2812.14   847.9  2813.8   941.1 2846.66   984.3 2869.59  1004.3 2871.38
  1019.9 2883.88  1070.8 2911.12  1087.1  2917.3  1107.1 2918.43  1406.7 3066.05
#Mann= 5 ,-1 , 0
       0      .1       0  130.12      .1       0   655.8    .045       0
     682      .1       0   810.6      .1       0
Bank Sta=655.8,682
XS Rating Curve= 0 ,0
Exp/Cntr=0.3,0.1

Type RM Length L Ch R = 1 ,14824   ,217.4,213.8,213.6
XS GIS Cut Line= 4
     2058084.236       365795.14     2057595.475      365501.274
     2057414.283       365353.58     2056981.859      365294.197
#Sta/Elev= 30
       0 2944.34    60.9 2915.56     151 2881.09   170.2 2879.49   185.5 2869.81
     271 2838.18     308 2829.19   353.9 2808.04   365.4 2798.84   388.4 2797.83
   420.8 2780.92   461.1 2770.04   542.7 2766.62   648.4 2768.07   663.8  2768.6
   684.5 2779.09   710.5 2782.82   728.9 2791.76   750.1 2793.91   762.8 2801.55
   804.9 2810.98   848.4 2841.38   868.8 2844.29     891 2857.38     934 2868.58
   973.6 2896.66   996.9 2898.96  1059.9 2936.62  1172.5 2979.44  1240.5  3017.9
#Mann= 5 ,-1 , 0
       0      .1       0  114.82      .1       0   648.4    .045       0
   663.8      .1       0  732.43      .1       0
#XS Ineff= 2 , 0
          583.65  2770.7
Permanent Ineff=
       F       F
Bank Sta=648.4,663.8
XS Rating Curve= 0 ,0
Exp/Cntr=0.3,0.1

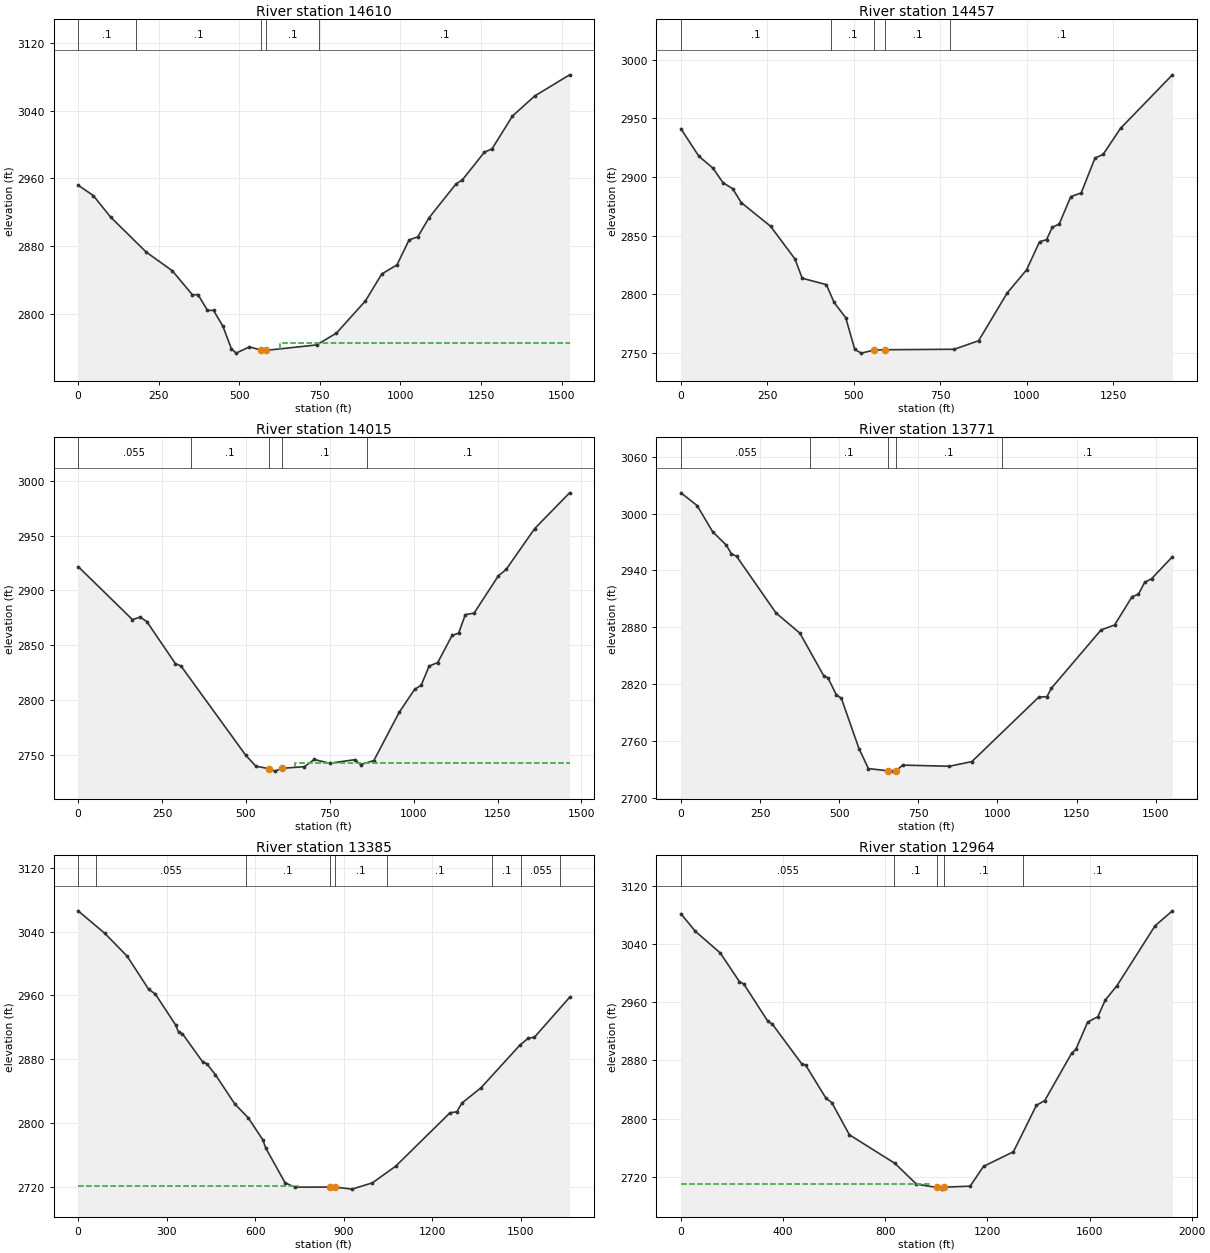
Type RM Length L Ch R = 1 ,14610   ,152.8,152.7,151.7
XS GIS Cut Line= 4
      2058184.97      365717.712     2057852.249      365448.904
     2057489.452      365253.407      2056825.89      365084.227
#Sta/Elev= 30
       0 2952.12    47.1 2939.84   100.6 2914.56   211.5  2873.1   292.2 2851.17
   354.8 2822.71   371.8 2823.06   401.3 2804.54   420.2 2804.36     449 2785.88
   475.6 2759.11   490.2 2754.01   531.1 2761.38   568.4 2757.59   581.52757.226
   739.6 2763.66   801.4 2777.61   891.2 2815.57     942 2847.37   989.4 2858.14
  1026.6 2887.46  1053.7 2891.22  1088.5 2913.57  1172.2 2953.53  1192.2 2958.42
  1260.2 2990.93    1284 2994.94  1347.5 3033.62    1416 3057.17  1524.6 3082.23
#Mann= 5 ,-1 , 0
       0      .1       0  179.43      .1       0   568.4    .045       0
   581.5      .1       0  747.33      .1       0
#XS Ineff= 2 , 0
                          627.17          2765.9
Permanent Ineff=
       F       F
Bank Sta=568.4,581.5
XS Rating Curve= 0 ,0
Exp/Cntr=0.3,0.1

Type RM Length L Ch R = 1 ,14457   ,445.9,442.6,435.6
XS GIS Cut Line= 4
2058290.29748484365595.5316353972057994.97970397365364.966129719
2057438.89305445365063.2736794932057033.32042896364984.999922542
#Sta/Elev= 30
       0 2941.25    51.9 2917.78    92.7 2907.65   121.5 2895.25   149.6 2890.14
   174.5 2878.25   259.1 2858.12   329.1 2830.46   350.7  2813.8   420.4 2808.37
   442.8 2793.18   476.4 2780.14   502.5 2753.16   521.2 2749.99   558.5 2752.59
     5912752.877   789.9 2753.29   860.3 2760.52   942.9 2801.21   998.9 2820.92
  1036.6 2844.94  1056.6 2846.63  1073.3 2857.22  1093.4 2860.03  1126.8  2883.4
  1156.8  2886.5  1196.9 2916.33  1220.3 2919.35  1270.5 2941.56  1420.4 2987.18
#Mann= 5 ,-1 , 0
       0      .1       0  432.84      .1       0   558.5    .045       0
     591      .1       0  778.92      .1       0
Bank Sta=558.5,591
XS Rating Curve= 0 ,0
Exp/Cntr(USF)=0,0
Exp/Cntr=0.3,0.1

Type RM Length L Ch R = 1 ,14015   ,243.2,244,244.7
XS GIS Cut Line= 2
 2058451.2195178364866.5243760982056988.15113908364932.323747628
#Sta/Elev= 30
       0 2921.75   161.9  2873.3   184.9 2875.55   204.6 2871.51     290 2833.11
   306.4 2831.01     499 2749.67   529.8 2739.47   568.22737.224   585.6 2734.97
   608.6 2737.53   674.3 2739.06   703.8 2745.61   749.1 2742.15   825.3 2745.44
   841.8 2740.95   881.2  2744.6   956.7 2788.62  1002.7 2809.57  1022.4 2813.42
  1045.9 2830.86  1071.6 2834.09  1114.3 2858.79    1134 2860.99  1153.8  2877.8
    1180 2879.23  1252.3 2913.26  1275.3 2919.03  1360.7 2956.43  1464.5 2989.02
#Mann= 5 ,-1 , 0
       0    .055       0  335.04      .1       0   568.2    .045       0
   608.6      .1       0  860.16      .1       0
#XS Ineff= 2 , 0
                          645.61         2742.59
Permanent Ineff=
       F       F
Bank Sta=568.2,608.6
XS Rating Curve= 0 ,0
Exp/Cntr(USF)=0,0
Exp/Cntr=0.3,0.1

Type RM Length L Ch R = 1 ,13771   ,382.4,385.8,381.8
XS GIS Cut Line= 4
     2058517.691      364646.239     2057978.194      364655.638
     2057564.643      364646.239     2056964.994      364642.479
#Sta/Elev= 30
       0 3021.82    51.1 3008.43   100.3 2980.78     143 2966.78   159.4 2957.58
   175.8 2954.86   300.5 2895.03   375.9 2873.71   451.4 2828.68   464.5  2826.6
   490.7 2808.93   507.2 2804.77   562.7 2751.83   592.5 2730.76   653.62728.514
   671.3 2728.11   679.62728.335   700.8 2734.47   848.5 2733.25   919.4 2738.21
  1130.7 2806.19  1156.9 2806.78    1170 2815.39  1327.5 2877.09  1370.2 2882.32
  1425.9 2912.35  1445.6 2914.68  1465.3 2927.34  1487.1 2931.18  1552.9 2954.35
#Mann= 5 ,-1 , 0
       0    .055       0  409.17      .1       0   653.6    .045       0
   679.6      .1       0 1016.02      .1       0
Bank Sta=653.6,679.6
XS Rating Curve= 0 ,0
Exp/Cntr=0.3,0.1

Type RM Length L Ch R = 1 ,13385   ,416.7,421.1,417.2
XS GIS Cut Line= 4
2058610.12798788 364321.081099572057941.61285631364298.454433578
2057456.16802231364335.4798870192056946.03955268 364353.99261374
#Sta/Elev= 30
       0 3066.09    91.1 3037.66   166.6 3009.03   239.4 2967.48   261.8 2961.71
   330.3 2923.05   340.6 2913.78   353.7 2911.89   422.6 2876.37   435.8 2874.42
   465.3 2860.56     531 2823.87   576.9 2806.32   626.2 2778.74     636 2768.55
   701.7 2724.82   734.9 2719.35   855.4 2719.48   869.6 2719.41   928.8 2716.87
   997.9 2724.81  1076.8 2745.68  1260.9  2812.7  1283.8 2813.91  1301.1 2824.84
  1365.9 2844.05  1497.2 2897.36  1526.8 2906.46  1546.5 2907.23  1666.2 2957.54
#Mann= 9 ,-1 , 0
       0      .1       0   60.24    .055       0  568.55      .1       0
   855.4    .045       0   869.6      .1       0 1047.93      .1       0
 1402.33      .1       0  1502.3    .055       0 1634.86      .1       0
#XS Ineff= 2 , 0
          746.74 2720.87
Permanent Ineff=
       F       F
Bank Sta=855.4,869.6
XS Rating Curve= 0 ,0
Exp/Cntr(USF)=0,0
Exp/Cntr=0.3,0.1

Type RM Length L Ch R = 1 ,12964   ,647.7,647.2,633.7
XS GIS Cut Line= 4
     2058715.276      363872.605     2057865.199      363916.467
     2057470.445      363920.644     2056793.725      363966.594
#Sta/Elev= 30
       0 3081.74    56.7  3057.6   153.8 3027.95   229.3 2988.33   245.7 2985.43
     341 2933.62   357.4  2930.3   472.4 2875.72   488.8 2873.38   567.7  2828.3
   590.7 2822.22   659.6 2777.87   837.9 2738.57   922.4 2709.98  1001.92705.472
  1020.8 2703.14  1030.6 2705.86  1132.4 2707.21  1184.9 2734.45  1301.9 2754.51
  1391.9 2818.37  1424.8 2824.98    1530 2890.07  1546.4 2895.36  1592.5 2932.77
  1632.6 2940.31  1661.5 2963.09  1707.6 2982.97  1856.1 3065.04  1924.3 3085.78
#Mann= 5 ,-1 , 0
       0    .055       0  834.53      .1       0  1001.9    .045       0
  1030.6      .1       0 1340.68      .1       0
#XS Ineff= 2 , 0
          976.09 2710.14
Permanent Ineff=
       F       F
Bank Sta=1001.9,1030.6
XS Rating Curve= 0 ,0
Exp/Cntr=0.3,0.1