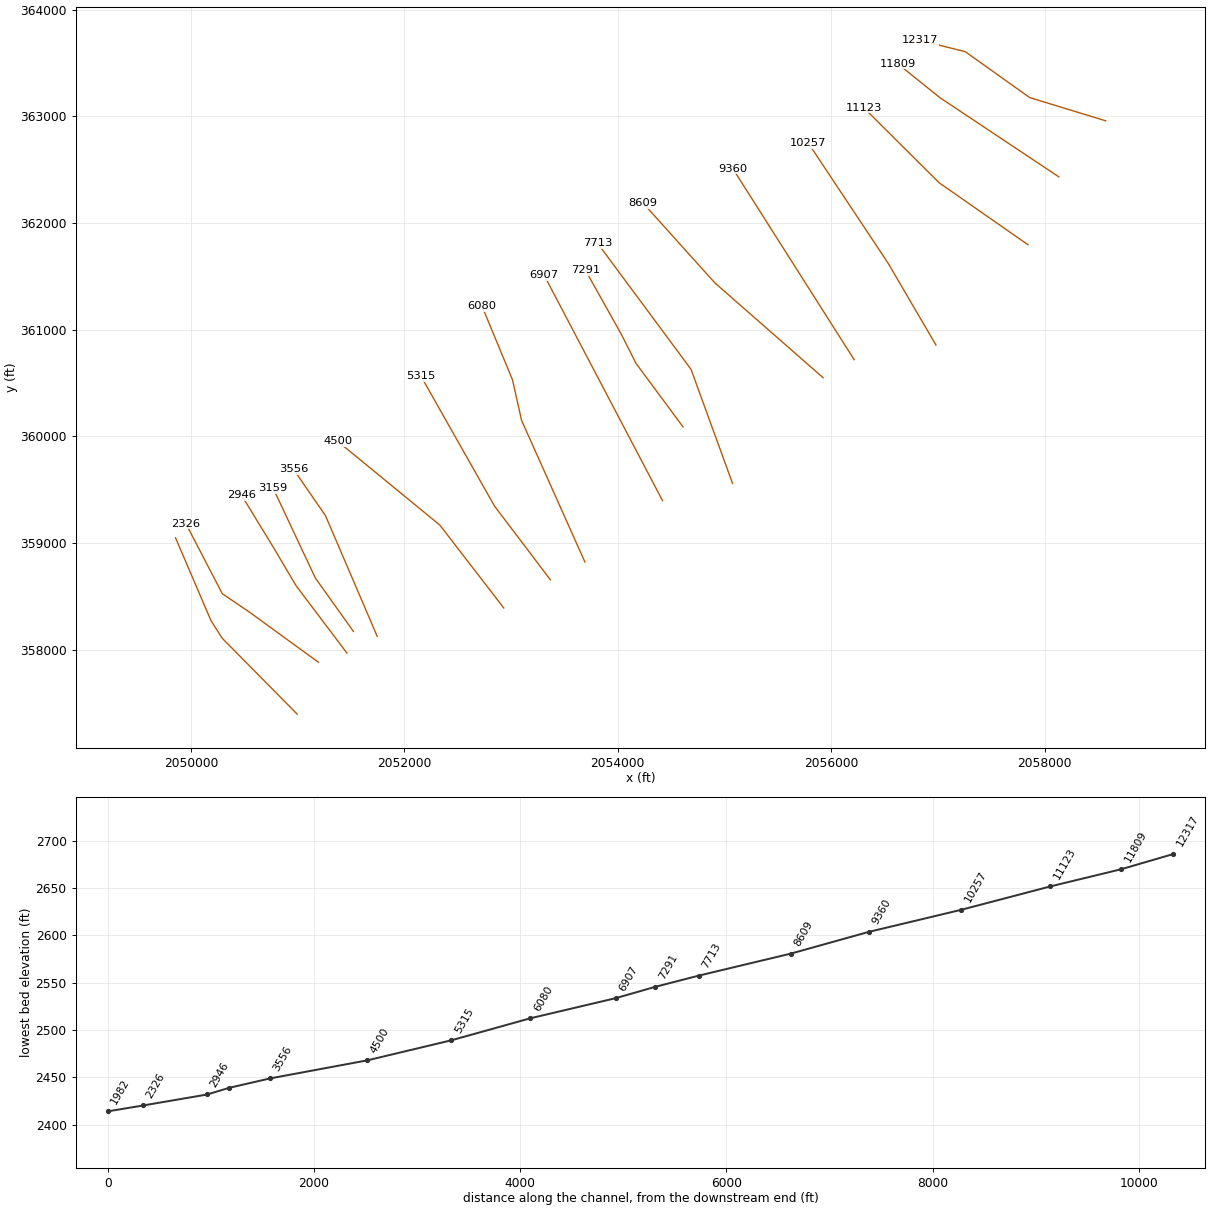
HEC-RAS study MILLCK2.prj: MILLCK2

--- MILLCK2.g01 (geometry) --- (continued)

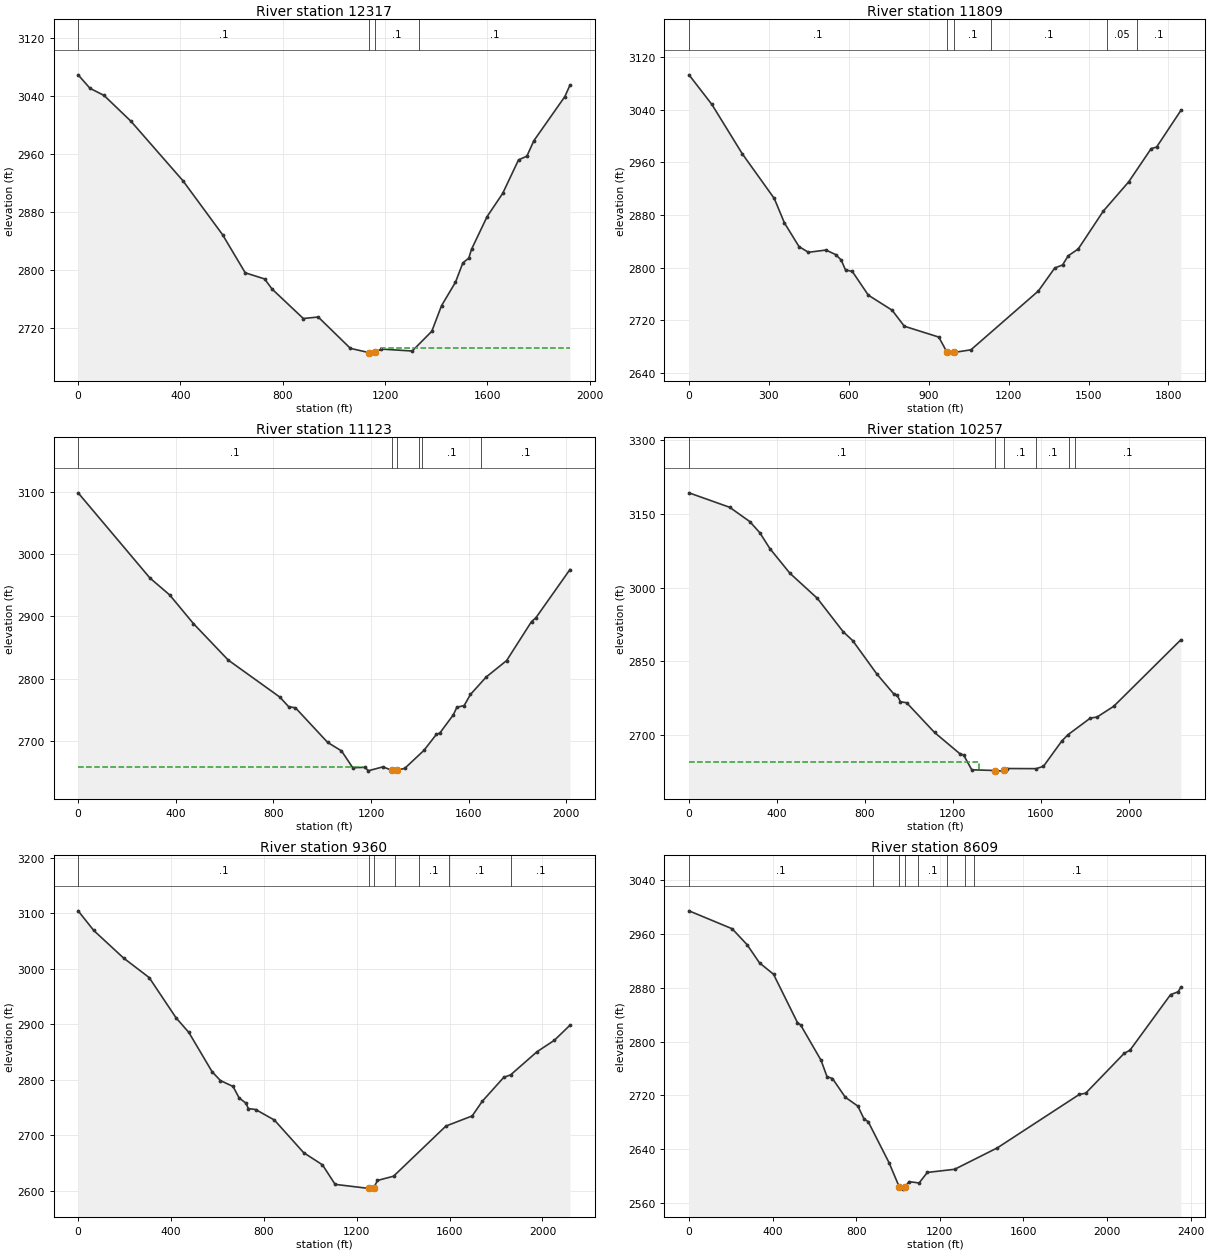
Type RM Length L Ch R = 1 ,12317   ,506.5,507.1,506.4
XS GIS Cut Line= 4
     2058573.248       362957.78     2057861.021      363174.999
     2057257.404      363605.259     2056833.409       363711.78
#Sta/Elev= 30
       0 3069.15    46.3  3050.6   101.2 3040.81     207 3005.04   409.9 2923.26
   564.5 2849.15   653.4 2796.52   728.9 2788.12   758.4 2774.12   880.6 2733.56
   938.6 2735.66  1064.6 2692.47  1135.62686.759  1151.9 2685.91  1161.22686.965
  1185.6  2691.5  1306.3 2688.82  1382.9 2716.02  1420.8 2751.19  1475.5  2783.6
  1504.3 2810.23  1527.4  2816.7  1538.1 2828.88    1599 2873.88  1659.9  2905.8
    1722 2952.05  1754.6 2957.14  1781.9  2978.4  1903.2 3039.27  1923.1 3054.96
#Mann= 4 ,-1 , 0
       0      .1       0  1135.6    .045       0  1161.2      .1       0
 1333.77      .1       0
#XS Ineff= 1 ,-1
 1185.98    1923 2692.34
Permanent Ineff=
       F
Bank Sta=1135.6,1161.2
XS Rating Curve= 0 ,0
Exp/Cntr=0.3,0.1

Type RM Length L Ch R = 1 ,11809   ,688.2,686,682.5
XS GIS Cut Line= 3
     2058134.599      362431.958     2057020.083      363174.013
     2056624.702      363492.037
#Sta/Elev= 30
       0 3092.99      86 3047.93   200.2 2972.84   320.2 2904.95   358.3 2867.84
   413.1 2831.75   448.6 2823.13   514.2 2826.55     551 2819.57   571.5 2811.39
   587.6 2796.19   612.9 2794.17   673.2 2757.98   762.7 2735.02   808.3 2710.74
   937.8  2694.2     9692670.825   987.5  2669.8   995.22670.816  1058.5 2674.88
  1311.7 2764.35    1373 2799.19  1402.5 2803.92  1423.6 2817.79  1461.3 2828.22
  1555.4 2885.79  1650.4 2930.09  1735.1 2980.85  1755.4 2983.12  1846.4 3038.75
#Mann= 6 ,-1 , 0
       0      .1       0     969    .045       0   995.2      .1       0
 1134.09      .1       0 1567.55     .05       0 1681.78      .1       0
Bank Sta=969,995.2
XS Rating Curve= 0 ,0
Exp/Cntr=0.3,0.1

Type RM Length L Ch R = 1 ,11123   ,867.8,866.6,861.4
XS GIS Cut Line= 3
     2057845.226       361795.91     2057011.488      362377.521
     2056303.814      363082.331
#Sta/Elev= 30
       0  3098.5   294.4 2961.61     375  2934.6   472.5 2888.51     615 2829.98
   826.5 2770.54   862.4 2755.19   890.5 2753.31  1022.6  2697.7    1079 2684.21
  1125.3 2657.12  1175.2 2657.79  1189.2 2652.31  1249.6 2658.54  1285.12652.824
  1291.7 2651.66  1304.72653.028  1338.3 2656.09    1417    2685  1467.9 2710.66
  1482.1 2712.87  1537.4 2742.08  1551.8 2754.17  1581.7 2756.92  1607.6 2774.81
  1672.2 2802.83  1755.7 2829.15  1857.8 2891.79  1875.4 2897.74  2015.3 2975.37
#Mann= 6 ,-1 , 0
       0      .1       0  1285.1    .045       0  1304.7      .1       0
 1396.02      .1       0 1407.82      .1       0 1652.35      .1       0
#XS Ineff= 2 , 0
         1171.19    2658
Permanent Ineff=
       F       F
Bank Sta=1285.1,1304.7
XS Rating Curve= 0 ,0
Exp/Cntr=0.3,0.1

Type RM Length L Ch R = 1 ,10257   ,893,896.9,892.6
XS GIS Cut Line= 3
     2056982.346      360856.392     2056534.309      361622.771
     2055787.581      362746.794
#Sta/Elev= 30
       0 3192.49   185.3 3163.04   276.7 3134.03   322.4 3111.26   367.7 3079.33
   458.9 3029.12   583.6 2978.17   701.2 2910.31   744.9 2892.02   854.2 2824.46
   931.7 2783.69   947.4 2781.15   961.6 2767.88     990 2765.89  1116.9 2705.44
  1231.4 2662.52  1249.6 2659.35  1286.2 2629.61  1392.1 2628.12  1427.8 2626.88
  1434.72628.246  1446.7 2632.19  1579.3 2631.91  1612.4 2636.69  1695.9 2688.11
  1723.6 2700.79  1825.9 2734.73  1856.2  2736.8  1932.2 2758.72  2237.2 2893.76
#Mann= 6 ,-1 , 0
       0      .1       0  1392.1    .045       0  1434.7      .1       0
 1579.01      .1       0 1729.01      .1       0 1756.95      .1       0
#XS Ineff= 2 , 0
         1320.54 2644.48
Permanent Ineff=
       F       F
Bank Sta=1392.1,1434.7
XS Rating Curve= 0 ,0
Exp/Cntr=0.3,0.1

Type RM Length L Ch R = 1 ,9360    ,744,751.4,750
XS GIS Cut Line= 2
     2056215.967      360718.837     2055080.154      362507.055
#Sta/Elev= 30
       0 3104.09    67.3 3068.75   195.8 3019.17   305.9 2984.08   422.2 2911.42
   476.9 2885.33   576.9 2814.78   612.9 2798.79   667.2 2788.24   693.3 2767.64
   721.9 2758.44   733.4 2748.43   764.5 2746.74   845.5 2727.74   971.4 2669.09
  1052.3 2647.27  1106.9 2612.11    12512604.865  1265.9 2603.54  1272.42604.953
  1289.2 2619.12  1358.5 2626.77    1584 2716.97  1697.3 2735.21    1740 2761.19
  1833.3 2804.59  1862.8 2809.07  1976.5 2850.68    2051 2871.19  2118.4 2898.34
#Mann= 7 ,-1 , 0
       0      .1       0    1251    .045       0  1272.4      .1       0
 1364.92      .1       0 1468.31      .1       0 1598.08      .1       0
 1863.56      .1       0
Bank Sta=1251,1272.4
XS Rating Curve= 0 ,0
Exp/Cntr=0.3,0.1

Type RM Length L Ch R = 1 ,8609    ,896.2,895.1,889.6
XS GIS Cut Line= 3
     2055925.136       360549.84     2054911.157      361438.054
     2054239.101      362184.783
#Sta/Elev= 30
       0 2994.33   206.6 2967.67     278 2943.98   337.4 2916.97   404.3 2900.12
   518.8 2828.27   533.7 2824.86   631.4 2772.34   660.2 2747.92   686.3  2745.1
   747.4 2717.37   808.1 2704.01   837.5 2684.83   856.9 2681.13   956.7 2620.16
  1006.92583.224  1022.2  2580.7  1033.12583.532  1052.7 2591.84  1100.7 2589.85
  1139.9  2605.5  1270.8 2610.19  1475.2 2642.08  1867.8  2721.6  1897.4  2723.2
  2081.6  2782.5  2109.3 2787.12  2303.5 2869.77  2340.1 2874.03  2352.6 2881.01
#Mann= 8 ,-1 , 0
       0      .1       0  882.57      .1       0  1006.9    .045       0
  1033.1      .1       0 1095.37      .1       0 1231.82      .1       0
 1322.01      .1       0 1361.73      .1       0
Bank Sta=1006.9,1033.1
XS Rating Curve= 0 ,0
Exp/Cntr=0.3,0.1

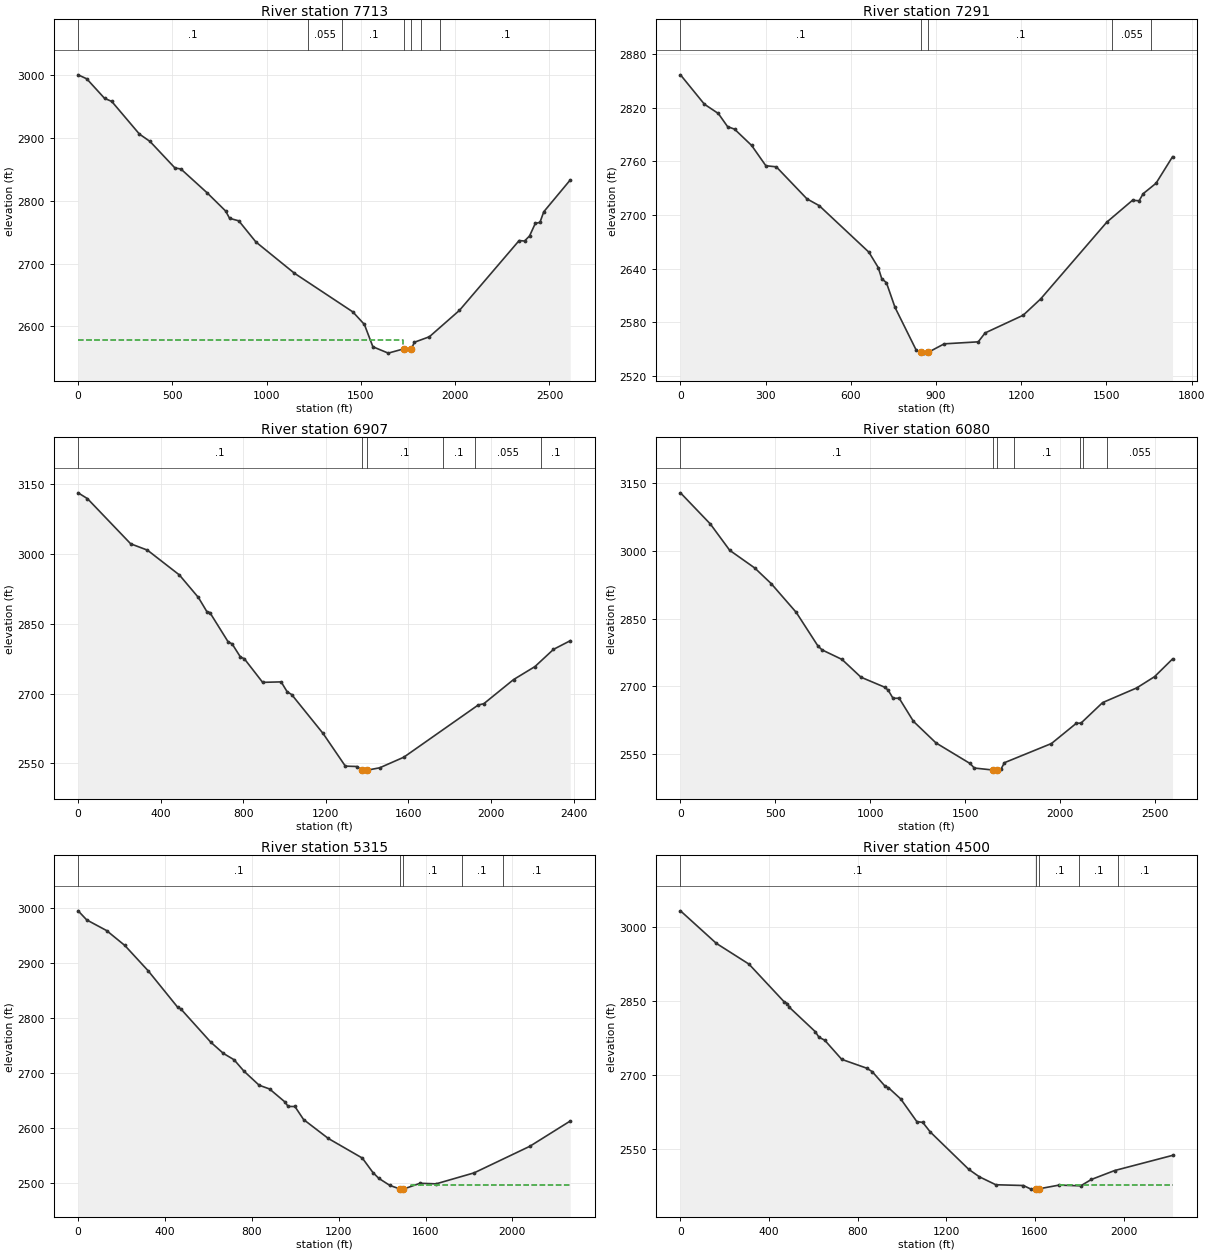
Type RM Length L Ch R = 1 ,7713    ,422.6,422.1,418
XS GIS Cut Line= 3
     2055076.223      359559.443     2054687.139      360628.443
     2053810.715      361811.418
#Sta/Elev= 30
       0 3000.53    45.7 2994.16   139.9 2963.17   178.4 2958.14     325 2906.15
   380.8 2894.55   513.5 2852.19   544.9 2850.61   684.6  2812.5   782.1 2783.71
   803.3 2772.04   852.2    2768   942.9 2734.34  1146.8 2684.66  1457.1 2623.01
  1518.2 2603.04  1563.3  2567.5  1644.7 2557.37  1730.7  2564.5  1767.4 2564.02
  1783.2 2574.65    1863 2583.46  2022.5 2625.49    2339 2736.65  2367.6 2735.87
  2394.3 2744.02  2424.8    2764  2449.3 2765.52  2469.7 2782.48  2609.9 2833.05
#Mann= 7 ,-1 , 0
       0      .1       0 1218.13    .055       0 1400.45      .1       0
  1730.7    .045       0  1767.4      .1       0 1820.23    .055       0
 1921.74      .1       0
#XS Ineff= 2 , 0
         1720.75 2578.12
Permanent Ineff=
       F       F
Bank Sta=1730.7,1767.4
XS Rating Curve= 0 ,0
Exp/Cntr=0.3,0.1

Type RM Length L Ch R = 1 ,7291    ,383.8,384.6,384.2
XS GIS Cut Line= 4
     2054612.287      360089.099     2054171.064      360685.036
     2054030.676      360962.948     2053698.326       361556.02
#Sta/Elev= 30
       0 2856.98    84.2  2824.1   133.2 2813.72   165.9    2799   190.4 2796.18
   250.6 2777.92   300.6 2755.24   337.4 2754.02   445.3 2718.18   488.4  2710.6
   663.4 2658.52   696.3 2641.34   708.8 2628.72   725.2 2624.37   755.4 2596.73
   829.7  2549.1   846.42546.264   859.1 2545.52   872.62546.458   928.6 2555.91
  1048.5 2558.16  1072.7 2568.12  1206.7 2587.92  1268.3 2606.19  1501.5 2692.21
  1591.7 2716.58  1614.9 2716.05  1629.3 2723.97  1674.5  2735.6  1732.7 2765.34
#Mann= 5 ,-1 , 0
       0      .1       0   846.4    .045       0   872.6      .1       0
 1520.43    .055       0 1656.24      .1       0
Bank Sta=846.4,872.6
XS Rating Curve= 0 ,0
Exp/Cntr=0.3,0.1

Type RM Length L Ch R = 1 ,6907    ,828.7,826.9,822.4
XS GIS Cut Line= 2
     2054419.888      359398.306     2053311.586      361508.797
#Sta/Elev= 30
       0 3131.94    45.2 3119.41   254.5 3022.33   335.6 3008.71   490.2 2955.44
   582.6 2906.88   623.3 2876.71   638.1 2874.51     727 2811.27   745.6 2807.34
   786.3 2778.86   804.8 2775.28   893.8 2724.41   983.4 2725.43  1012.6 2704.14
  1034.5 2698.13  1186.5 2614.53  1294.4 2544.29  1351.7 2543.46  1373.92534.902
  1390.3 2533.52  1398.92535.468  1460.8 2540.68  1577.6 2563.45  1938.3 2675.75
  1965.1 2678.45  2109.3 2730.36  2212.9 2758.32  2302.8 2795.34  2383.8 2813.89
#Mann= 6 ,-1 , 0
       0      .1       0  1373.9    .045       0  1398.9      .1       0
  1769.2      .1       0 1920.27    .055       0 2244.49      .1       0
Bank Sta=1373.9,1398.9
XS Rating Curve= 0 ,0
Exp/Cntr=0.3,0.1

Type RM Length L Ch R = 1 ,6080    ,752.8,765,762.1
XS GIS Cut Line= 4
     2053692.615      358823.079     2053099.588      360149.303
      2053013.33      360532.075     2052727.599      361222.142
#Sta/Elev= 30
       0 3128.42   157.5 3059.35   259.3 3001.18   390.9 2962.12   477.8 2927.45
   609.9 2863.66   724.2 2789.26     746 2780.65     851 2759.53   950.7 2720.24
  1076.3 2697.99  1094.4 2691.28  1119.6 2673.52  1151.9 2673.72  1227.4 2622.37
    1346 2574.69  1525.3 2529.17  1547.9 2519.12  1645.72514.745  1652.2 2512.28
  1668.6 2513.73  1687.9 2516.26  1706.4 2530.94  1954.3 2573.44  2084.8  2618.1
    2110 2618.67  2223.7 2664.04  2403.8 2696.61  2497.2 2721.41    2592 2760.61
#Mann= 7 ,-1 , 0
       0      .1       0  1645.7    .045       0  1668.6      .1       0
 1756.93      .1       0 2104.13    .055       0 2118.17      .1       0
 2246.63    .055       0
Bank Sta=1645.7,1668.6
XS Rating Curve= 0 ,0
Exp/Cntr=0.3,0.1

Type RM Length L Ch R = 1 ,5315    ,812,815,817.5
XS GIS Cut Line= 3
     2053369.146      358655.954     2052846.204      359346.021
     2052156.137      360564.421
#Sta/Elev= 30
       0 2994.22    39.6  2977.7   130.6  2958.5   214.9 2931.39     323 2885.14
   458.4 2819.18   472.5  2816.3   610.6 2755.85   668.8 2735.43   718.2 2723.86
   763.4 2703.26   833.4 2677.69   881.4 2670.86   952.5 2647.24     967 2639.09
   998.3 2639.03  1038.2 2615.36  1152.3 2580.97  1308.8  2545.4  1357.8 2519.05
  1384.4  2508.7  1435.7  2495.7  1482.42489.294  1494.2 2489.04  1497.42489.083
  1575.2 2499.65  1648.2 2498.62  1823.8  2518.6  2080.4 2566.87  2266.1 2612.64
#Mann= 5 ,-1 , 0
       0      .1       0  1482.4    .045       0  1497.4      .1       0
 1766.42      .1       0 1954.35      .1       0
#XS Ineff= 2 , 0
                         1534.99         2496.62
Permanent Ineff=
       F       F
Bank Sta=1482.4,1497.4
XS Rating Curve= 0 ,0
Exp/Cntr=0.3,0.1

Type RM Length L Ch R = 1 ,4500    ,944.8,943.7,937.4
XS GIS Cut Line= 3
     2052932.463      358391.787     2052334.045      359168.113
      2051374.42      359955.221
#Sta/Elev= 30
       0 3031.78   162.2 2965.73   309.2  2923.8     468 2847.42   482.3 2843.94
   491.6 2836.25   608.3 2787.04     625 2775.69   651.3 2769.59   727.9 2730.81
   840.2 2713.01   865.7 2705.86   924.4 2676.02   938.4 2673.56   994.5 2650.47
  1066.8  2604.8  1093.9    2603  1127.4 2583.77  1301.8 2507.77  1349.3 2492.83
  1423.5 2476.73  1547.9 2475.19  1582.1 2467.85  1604.72468.886  1619.72468.608
  1709.2 2476.02  1806.7 2474.49  1854.7  2487.4  1959.5 2505.47  2221.3 2536.23
#Mann= 5 ,-1 , 0
       0      .1       0  1604.7    .045       0  1619.7      .1       0
 1801.18      .1       0 1974.48      .1       0
#XS Ineff= 2 , 0
                         1710.82            2476
Permanent Ineff=
       F       F
Bank Sta=1604.7,1619.7
XS Rating Curve= 0 ,0
Exp/Cntr=0.3,0.1

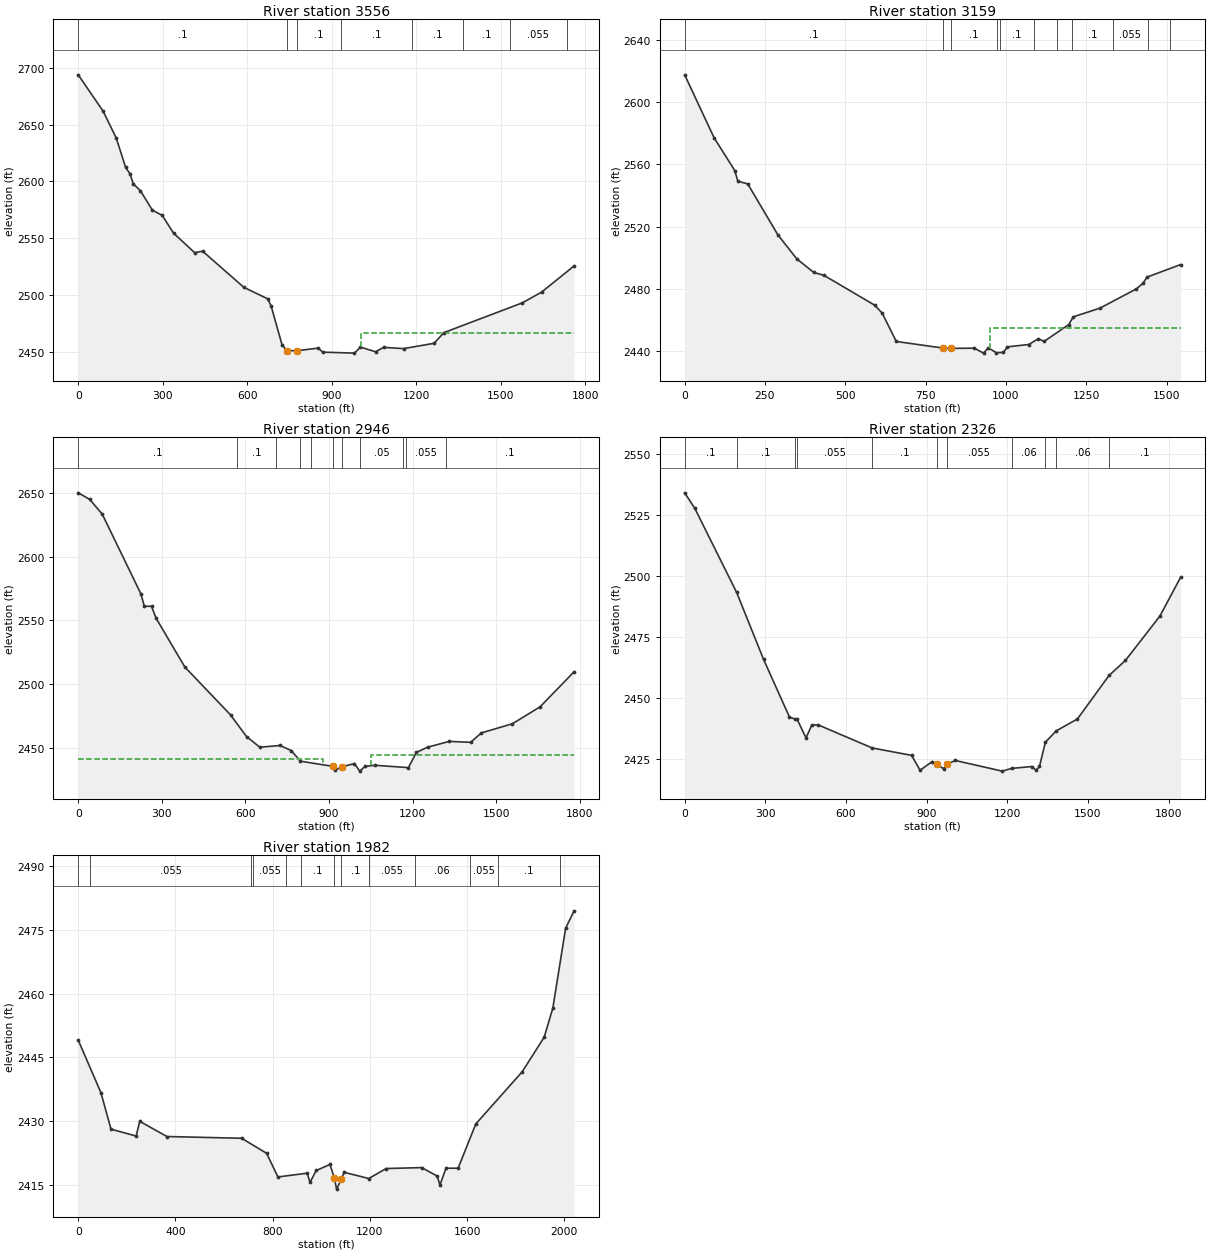
Type RM Length L Ch R = 1 ,3556    ,396.8,396.6,400.3
XS GIS Cut Line= 3
      2051746.14      358126.596     2051261.421      359257.606
      2050960.11       359694.29
#Sta/Elev= 30
       0 2693.85    88.6 2661.79     135 2638.18   168.4 2612.29   183.4 2606.86
   195.6 2597.92   220.9 2591.73   263.4 2574.62   298.3 2570.09   338.4 2554.46
   413.3 2537.23   441.9  2538.5   588.3 2506.65   673.1 2496.56   684.7 2490.45
   723.9 2456.03   740.6 2450.96   777.5 2450.83   852.4 2453.18     868 2449.61
   980.9 2448.74  1002.3 2454.01  1055.9 2449.94  1084.4 2453.81  1155.8 2452.73
  1263.4 2457.38  1298.7 2466.82  1577.6 2493.07  1645.5 2502.47  1761.1 2525.57
#Mann= 8 ,-1 , 0
       0      .1       0   740.6    .045       0   777.5      .1       0
  933.99      .1       0 1185.94      .1       0 1367.41      .1       0
 1532.55    .055       0 1735.79      .1       0
#XS Ineff= 2 , 0
                         1004.77         2466.56
Permanent Ineff=
       F       F
Bank Sta=740.6,777.5
XS Rating Curve= 0 ,0
Exp/Cntr=0.3,0.1

Type RM Length L Ch R = 1 ,3159    ,214.6,213.6,217.2
XS GIS Cut Line= 3
2051522.98499918358172.7121700342051166.44359568 358673.24144803
2050771.04832128359514.313476807
#Sta/Elev= 30
       0 2617.53    91.7 2577.04     156 2556.07   165.5 2549.23   196.4 2547.46
   290.1 2514.78   348.9 2499.36   401.8 2490.64   433.6 2488.76   591.4  2469.6
   614.8 2464.51   658.7  2446.3   803.7 2442.08   829.3 2441.84   901.6    2442
   930.6 2438.81   945.1 2442.25   969.9 2439.07   992.3 2439.29  1004.4 2442.83
    1071 2444.34    1101 2448.04  1119.1 2446.37  1195.3 2457.08  1209.8  2462.1
  1293.2 2467.73  1406.4 2480.09  1427.3 2483.78  1438.9 2487.59  1543.9 2495.68
#Mann= 11 ,-1 , 0
       0      .1       0   803.7    .045       0   829.3      .1       0
  970.92      .1       0  981.85      .1       0 1087.77      .1       0
 1157.68    .055       0 1205.45      .1       0 1333.52    .055       0
 1440.81      .1       0 1509.36     .06       0
#XS Ineff= 2 , 0
                          948.93         2454.64
Permanent Ineff=
       F       F
Bank Sta=803.7,829.3
XS Rating Curve= 0 ,0
Exp/Cntr(USF)=0,0
Exp/Cntr=0.3,0.1

Type RM Length L Ch R = 1 ,2946    ,614,619.9,621.2
XS GIS Cut Line= 4
     2051462.994      357968.473     2050985.481      358601.621
     2050780.327       358948.26     2050476.134      359446.996
#Sta/Elev= 30
       0 2649.94    41.1 2644.83    86.3 2633.22     225 2570.71   237.3    2561
   263.1 2560.99   279.5 2551.65   382.5 2513.43   546.6 2475.87   604.1 2458.85
   651.9 2450.51   724.6 2451.85   764.4 2447.85   797.8 2439.54   913.8 2435.49
   922.7 2432.69     946 2435.12   991.4 2437.68  1010.4 2431.75  1029.7 2435.51
  1065.5 2436.33  1185.2  2434.5  1213.9 2446.44  1253.9  2450.5  1331.7 2455.06
  1408.6 2454.34    1447 2461.72  1558.5  2468.9  1657.9  2482.2    1780 2509.71
#Mann= 11 ,-1 , 0
       0      .1       0  571.31      .1       0  711.36     .06       0
   797.2      .1       0  833.73      .1       0   913.8    .045       0
     946      .1       0 1011.07     .05       0 1166.14     .06       0
 1176.23    .055       0 1319.24      .1       0
#XS Ineff= 2 , 0
          878.32 2441.46 1052.51          2444.7
Permanent Ineff=
       F       F
Bank Sta=913.8,946
XS Rating Curve= 0 ,0
Exp/Cntr=0.3,0.1

Type RM Length L Ch R = 1 ,2326    ,346.3,344.2,331.3
XS GIS Cut Line= 4
     2051193.941      357884.308     2050543.568      358357.046
     2050294.307      358526.086     2049953.362      359182.189
#Sta/Elev= 30
       0 2534.16    37.5 2527.84   193.4 2493.34   293.2 2465.99   389.8 2442.29
   410.3 2441.48   417.9 2441.44   451.4 2433.78   472.4 2438.97     496 2439.12
   697.4 2429.65   843.9 2426.62   875.6 2420.52   920.8  2424.1  938.03 2423.12
   962.8 2421.11   974.7 2422.95  1006.4 2424.53  1180.9 2420.16  1216.3 2421.28
  1290.7 2422.04  1307.4 2420.51  1319.6 2422.07  1341.5 2431.98  1382.1 2436.66
  1460.7 2441.52  1578.6 2459.37  1639.4 2465.51  1767.5 2483.67  1844.6 2499.57
#Mann= 11 ,-1 , 0
       0      .1       0   193.4      .1       0   410.3     .06       0
   417.9    .055       0   697.4      .1       0  938.03    .045       0
   974.7    .055       0  1216.3     .06       0  1341.5      .1       0
  1382.1     .06       0  1578.6      .1       0
Bank Sta=938.03,974.7
XS Rating Curve= 0 ,0
Exp/Cntr=0.3,0.1

Type RM Length L Ch R = 1 ,1982    ,421.2,425.9,419.7
XS GIS Cut Line= 4
     2050996.251      357397.245     2050294.307      358107.785
     2050188.299      358273.959     2049855.949      359050.396
#Sta/Elev= 30
       0 2449.03    93.5 2436.65   134.9 2428.07   238.2 2426.44   253.2 2429.91
   364.9 2426.33   672.4 2425.92   775.1 2422.38   821.8 2416.81   942.2  2417.7
   953.8 2415.54   979.4 2418.33  1035.9 2419.75  1053.72416.595  1063.2 2413.94
  1082.82416.345  1094.3  2417.9  1195.5 2416.44  1266.9 2418.79  1413.2 2419.01
  1477.5    2417  1488.2 2414.88  1513.1 2418.87  1563.1 2418.87  1635.8 2429.29
  1827.3 2441.62  1917.3 2449.74  1952.7 2456.55  2005.6 2475.44  2040.5 2479.49
#Mann= 13 ,-1 , 0
       0      .1       0   50.04    .055       0  709.05     .06       0
  719.41    .055       0  855.97     .06       0  916.89      .1       0
  1053.7    .045       0  1082.8      .1       0 1198.25    .055       0
 1383.68     .06       0  1611.5    .055       0 1726.53      .1       0
 1981.39     .06       0
Bank Sta=1053.7,1082.8
XS Rating Curve= 0 ,0
Exp/Cntr=0.5,0.3