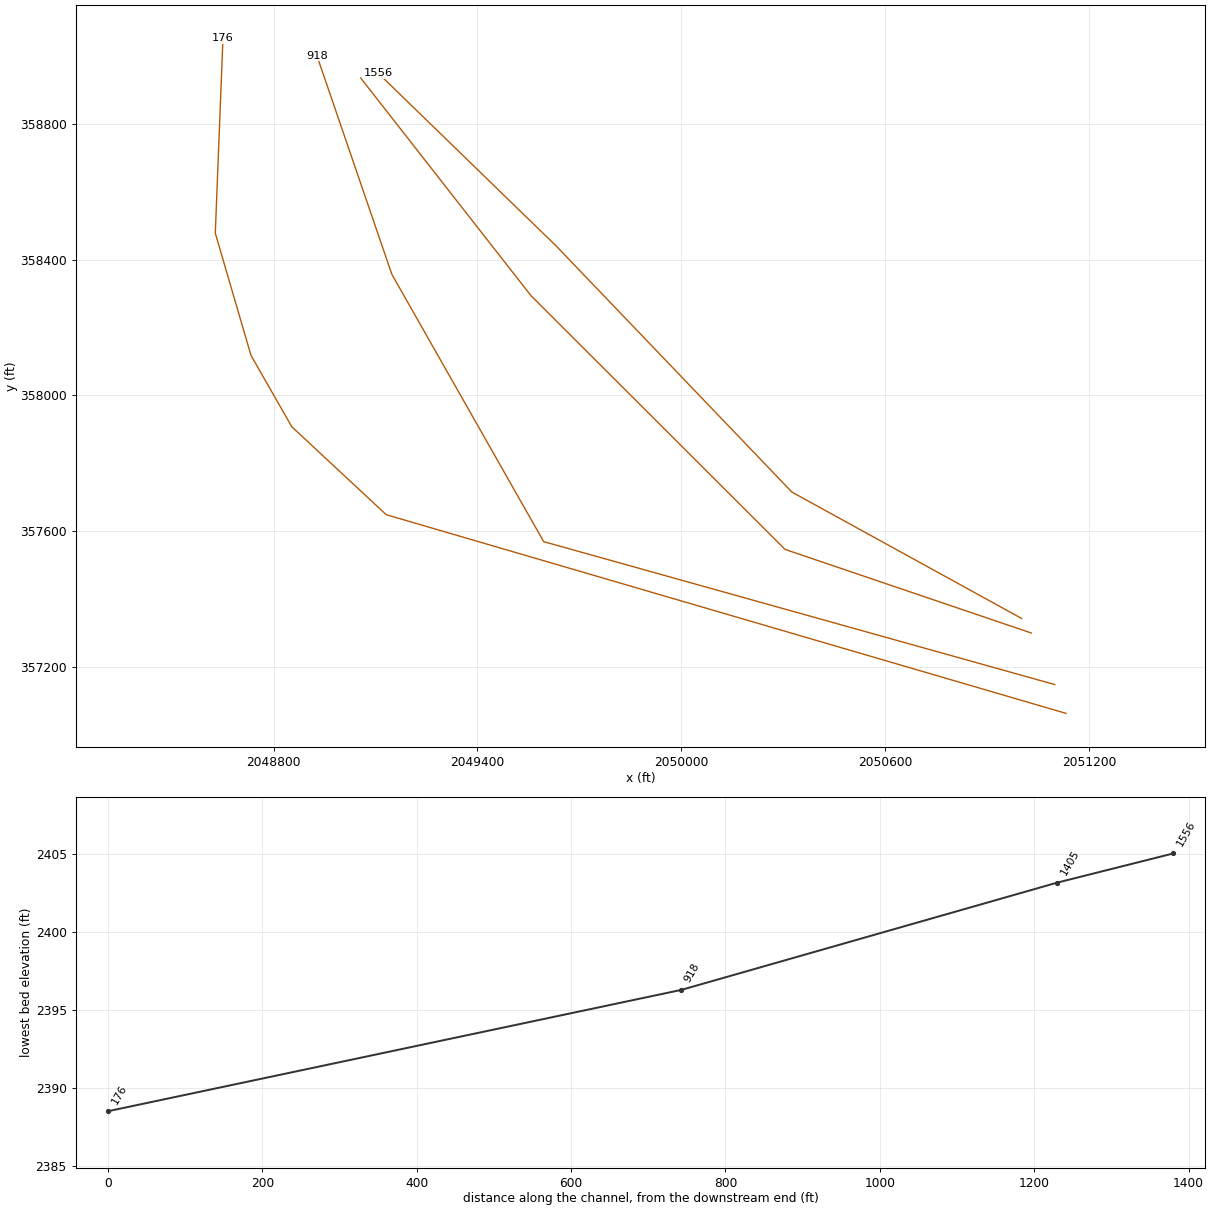
HEC-RAS study MILLCK2.prj: MILLCK2

--- MILLCK2.g01 (geometry) --- (continued)

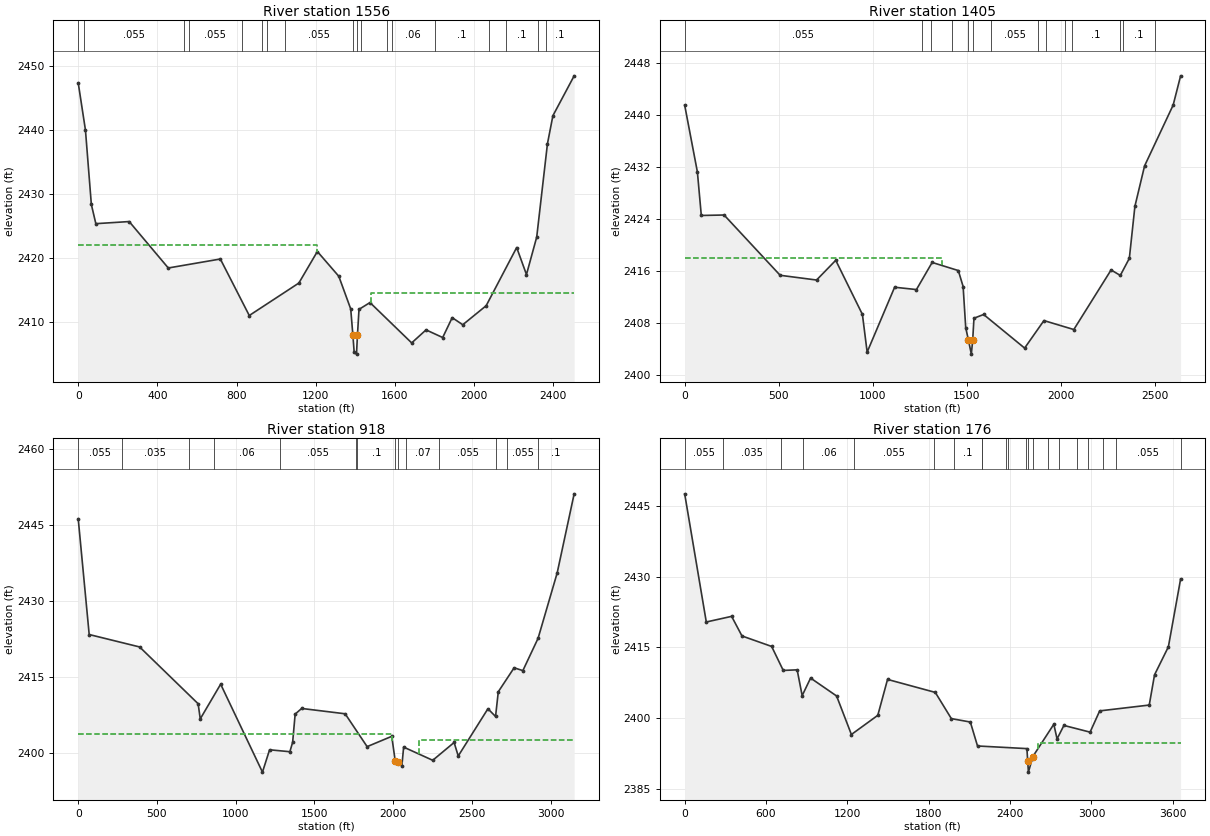
Type RM Length L Ch R = 1 ,1556    ,149.9,150.9,150.4
XS GIS Cut Line= 4
     2051001.981      357342.808     2050325.822      357715.269
     2049632.473      358440.134     2049108.164      358950.118
#Sta/Elev= 30
       0 2447.35    36.6 2439.98    66.4 2428.38    89.1 2425.39   257.6 2425.72
   455.2 2418.48   718.3 2419.88   864.5 2411.07  1115.1 2416.13  1208.6 2421.05
    1317 2417.19  1377.3 2412.09  1388.2 2408.01  1394.8 2405.31  1406.5 2405.05
  1411.2 2407.96  1419.1 2412.03  1474.7 2413.09  1685.3  2406.8    1758 2408.83
  1842.1 2407.64  1890.1 2410.74  1943.5 2409.63  2061.8  2412.6    2216 2421.67
  2265.5 2417.46  2317.3  2423.3  2371.6 2437.86  2399.1 2442.22  2506.5 2448.44
#Mann= 18 ,-1 , 0
       0      .1       0    27.6    .055       0  535.42    .035       0
  558.41    .055       0   826.3    .035       0  928.45    .055       0
  951.94     .06       0 1044.88    .055       0  1388.2    .045       0
  1411.2    .055       0 1429.17    .035       0 1561.98    .055       0
 1583.61     .06       0 1801.86      .1       0 2074.45      .1       0
 2164.37      .1       0 2322.02      .1       0 2363.15      .1       0
#XS Ineff= 2 , 0
         1206.44 2422.02 1478.52         2414.57
Permanent Ineff=
       F       F
Bank Sta=1388.2,1411.2
XS Rating Curve= 0 ,0
Exp/Cntr=0.5,0.3

Type RM Length L Ch R = 1 ,1405    ,484.9,486.5,478.9
XS GIS Cut Line= 4
     2051030.632      357299.832     2050305.767      357546.229
     2049557.981      358294.015     2049056.592      358935.792
#Sta/Elev= 30
       0 2441.54    67.6 2431.25    88.4 2424.54   209.7 2424.61   507.7 2415.32
   701.4 2414.59   803.4 2417.63   945.2 2409.29   970.4 2403.48  1116.5 2413.48
  1232.5 2413.12  1316.1  2417.3  1455.2 2416.05  1480.8 2413.59  1494.7 2407.22
  1508.8 2405.37  1524.5 2403.17  1531.72405.339  1538.5  2408.7  1589.8 2409.28
  1807.9  2404.1  1910.6 2408.34  2069.5 2406.96  2267.7 2416.14  2316.8  2415.3
  2364.8 2417.93  2394.4 2425.95  2445.8 2432.18  2597.8 2441.55  2637.5 2446.06
#Mann= 14 ,-1 , 0
       0    .055       0 1260.88    .035       0 1308.43    .055       0
 1421.09    .035       0  1508.8    .045       0  1531.7    .035       0
 1630.55    .055       0 1880.99     .06       0 1920.11    .055       0
  2023.6      .1       0 2059.78      .1       0 2314.78      .1       0
 2330.24      .1       0 2501.42      .1       0
#XS Ineff= 2 , 0
         1367.54 2417.96  1590.2         2409.14
Permanent Ineff=
       F       F
Bank Sta=1508.8,1531.7
XS Rating Curve= 0 ,0
Exp/Cntr=0.5,0.3

Type RM Length L Ch R = 1 ,918     ,731.9,742.9,738.2
XS GIS Cut Line= 4
     2051099.394      357147.983     2049595.227       357569.15
     2049148.275      358357.046     2048927.664      359001.689
#Sta/Elev= 30
       0 2446.19    69.7 2423.39     390 2420.94   761.4 2409.76     775 2406.78
   904.5 2413.61    1170 2396.29  1215.2 2400.69    1344 2400.31  1361.6 2402.16
  1377.6 2407.72  1418.9 2408.83    1695 2407.78  1834.6 2401.31    1991 2403.34
  2013.32398.417  2032.92398.313  2055.1 2397.48  2066.4 2401.22  2251.2 2398.62
    2387 2402.13  2413.1 2399.47  2601.6 2408.77  2650.1 2407.25  2667.5 2412.12
    2768 2416.84  2823.5 2416.28  2920.2 2422.65  3041.4 2435.52  3149.2  2451.1
#Mann= 14 ,-1 , 0
       0    .055       0  275.96    .035       0  700.56    .055       0
  861.09     .06       0 1278.98    .055       0 1761.14     .06       0
  1772.6      .1       0  2013.3    .045       0  2032.9     .06       0
 2078.31     .07       0 2292.33    .055       0 2655.82    .035       0
 2721.74    .055       0 2920.95      .1       0
#XS Ineff= 2 , 0
         1995.14 2403.81 2165.24         2402.58
Permanent Ineff=
       F       F
Bank Sta=2013.3,2032.9
XS Rating Curve= 0 ,0
Exp/Cntr=0.3,0.1

Type RM Length L Ch R = 1 ,176     ,176,176,176
XS GIS Cut Line= 6
2051132.71898082357062.9724652842049131.66431379357648.647001978
2048853.84434125357907.6953547462048733.70597475358117.937496124
2048628.58490406358478.3525956282048651.11084778359052.764160462
#Sta/Elev= 30
       0 2447.67   159.4 2420.42   346.2 2421.62   422.6 2417.45   641.4 2415.22
   726.9 2410.12   829.5 2410.25   866.4 2404.76   928.5  2408.5  1120.3 2404.69
  1229.4  2396.5  1424.2 2400.58    1496 2408.21  1848.1 2405.45  1966.5 2399.88
  2106.6 2399.15  2159.5 2394.06  2523.9  2393.5 2529.512390.826  2534.9  2388.5
  2567.2  2391.8  2722.2 2398.68  2746.1 2395.56  2796.6 2398.43  2989.7    2397
  3060.5 2401.52  3425.9 2402.76    3465 2409.19    3567 2415.14  3657.3 2429.57
#Mann= 21 ,-1 , 0
       0    .055       0  284.87    .035       0  713.15    .055       0
  874.61     .06       0 1246.72    .055       0 1836.84     .06       0
 1986.83      .1       0 2192.52      .1       0 2192.52    .045       0
  2366.3      .1       0 2381.15    .045       0 2518.92      .1       0
 2529.51    .045       0  2567.2      .1       0 2676.89    .045       0
 2760.04     .07       0  2893.9      .1       0 2975.44    .055       0
 3083.08    .035       0 3181.25    .055       0 3657.29      .1       0
#XS Ineff= 2 , 0
                         2605.79         2394.68
Permanent Ineff=
       F       F
Bank Sta=2529.51,2567.2
XS Rating Curve= 0 ,0
Exp/Cntr(USF)=0,0
Exp/Cntr=0.3,0.1
LCMann Table=0

Chan Stop Cuts=-1
Use User Specified Reach Order=0
Composite Channel Slope=5